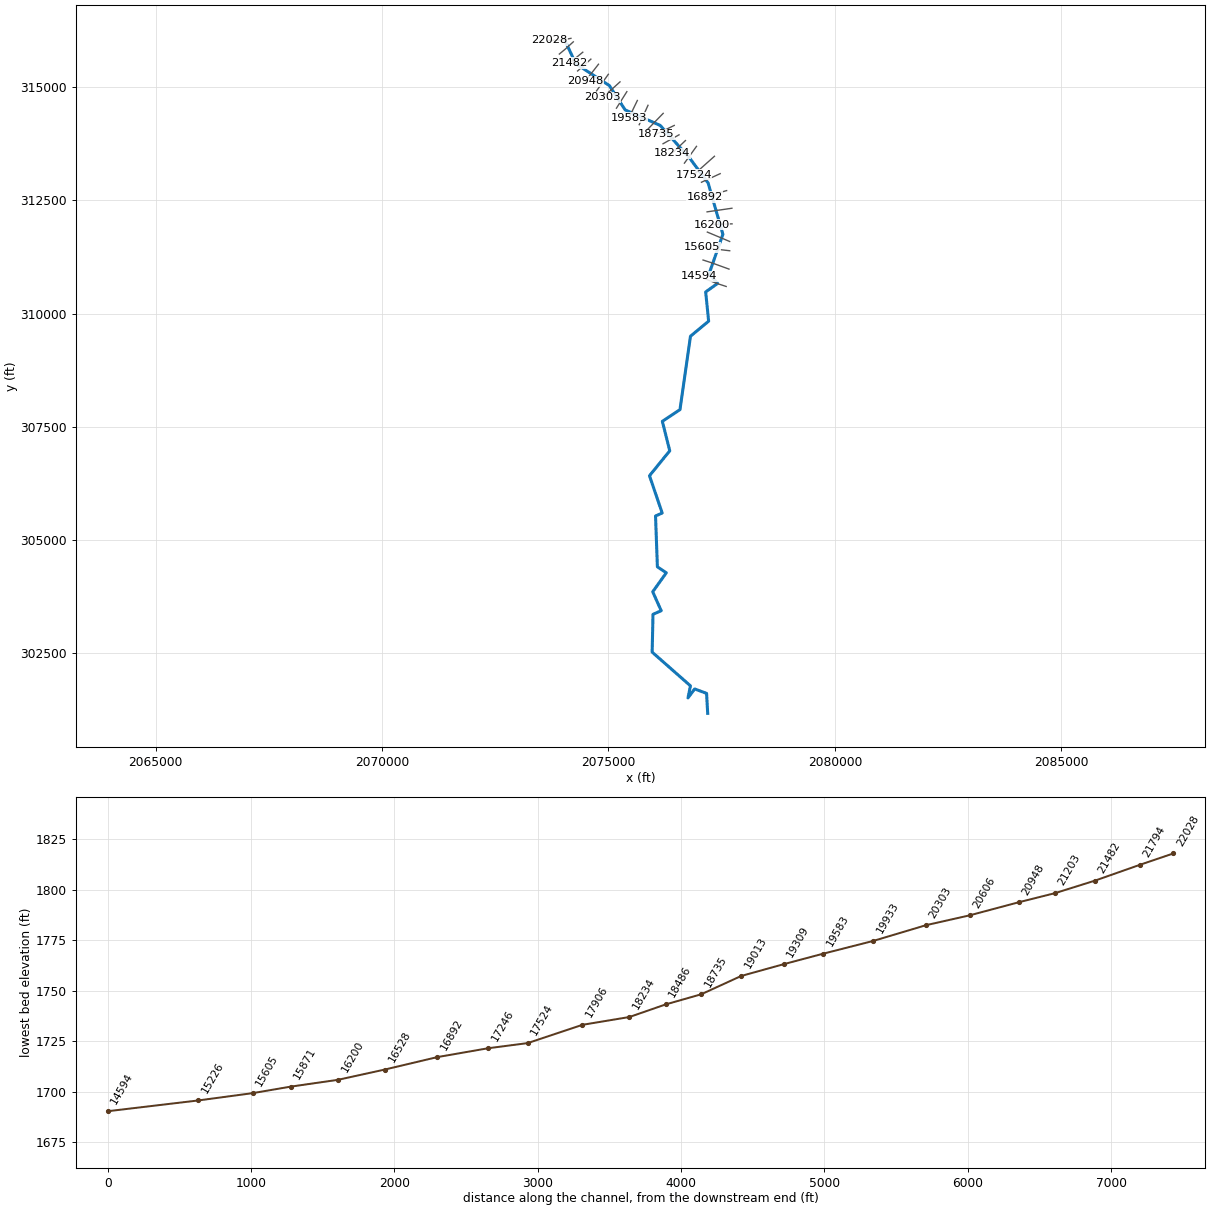
--- RENICKCK.prj (project) ---

Proj Title=RENICKCK
Current Plan=p01
Default Exp/Contr=0.3,0.1
English Units
Geom File=g01
Flow File=f01
Plan File=p01
Y Axis Title=Elevation
X Axis Title(PF)=Main Channel Distance
X Axis Title(XS)=Station
BEGIN DESCRIPTION:
Stream Name- Renick Creek
Flood Zone: Zone A
Greenbrier County, WV
County-Wide Study
WVDHSEM-2018-3, Flood Risk Project
HEC-RAS Version: 5.0.7
General Notes:
For the Hydrology Regression was used.
END DESCRIPTION:
DSS Export Rating Curves= 0
DSS Export Rating Curve Sorted= 0
DSS Export Volume Flow Curves= 0
DXF Filename=..\J2.
DXF OffsetX= 0
DXF OffsetY= 0
DXF ScaleX= 1
DXF ScaleY= 10

--- RENICKCK.p01 (plan) ---

Plan Title=Floodplain
Program Version=5.07
Short Identifier=Floodplain
Geom File=g01
Flow File=f01
Subcritical Flow
K Sum by GR= 0
Std Step Tol= 0.01
Critical Tol= 0.01
Num of Std Step Trials= 20
Max Error Tol= 0.3
Flow Tol Ratio= 0.001
Split Flow NTrial= 30
Split Flow Tol= 0.02
Split Flow Ratio= 0.02
Log Output Level= 0
Friction Slope Method= 1
Unsteady Friction Slope Method= 2
Unsteady Bridges Friction Slope Method= 1
Parabolic Critical Depth
Global Vel Dist= 0 , 0 , 0
Global Log Level= 0
CheckData=True
Encroach Param=-1 ,0,0, 0
Computation Interval=1MIN
Output Interval=1HOUR
Instantaneous Interval=1HOUR
Mapping Interval=1HOUR
Computation Time Step Use Courant=        0
Computation Time Step Use Time Series=    0
Computation Time Step Count To Double=0
Computation Time Step Max Doubling=0
Computation Time Step Max Halving=0
Computation Time Step Residence Courant=0
Run HTab= 0
Run UNet= 0
Run Sediment= 0
Run PostProcess= 0
Run WQNet= 0
Run RASMapper= 0
UNET Theta= 1
UNET Theta Warmup= 1
UNET ZTol= 0.02
UNET ZSATol= 0.02
UNET MxIter= 20
UNET Max Iter WO Improvement= 0
UNET MaxInSteps= 0
UNET DtIC= 0
UNET DtMin= 0
UNET MaxCRTS= 20
UNET WFStab= 2
UNET SFStab= 1
UNET WFX= 1
UNET SFX= 1
UNET 1D Methodology=Finite Difference
UNET DSS MLevel= 4
UNET Pardiso=0
UNET DZMax Abort= 100
UNET Use Existing IB Tables=-1
UNET Froude Reduction=False
UNET Froude Limit= 0.8
UNET Froude Power= 4
UNET D1 Cores= 0
UNET D2 Coriolis=0
UNET D2 Cores= 0
UNET D2 Theta= 1
UNET D2 Theta Warmup= 1
UNET D2 Z Tol= 0.01
UNET D2 Volume Tol= 0.01
UNET D2 Max Iterations= 20
UNET D2 Equation= 0
UNET D2 RampUpFraction=0.1
UNET D2 TimeSlices= 1
UNET D2 BCVolumeCheck=0
UNET D1D2 MaxIter= 0
UNET D1D2 ZTol=0.01
UNET D1D2 QTol=0.1
UNET D1D2 MinQTol=1
Write IC File= 0
Write IC File at Fixed DateTime=0
Write IC File at Sim End=0
Echo Input=False
Echo Parameters=False
Echo Output=False
Write Detailed= 0
HDF Write Warmup=0
HDF Write Time Slices=0
HDF Flush=0
HDF Face Node Velocities=0
HDF Compression= 1
HDF Chunk Size= 1
HDF Spatial Parts= 1
HDF Use Max Rows=0
HDF Fixed Rows= 1
Calibration Method= 0
Calibration Iterations= 20
Calibration Max Change=0.05
Calibration Tolerance=0.2
Calibration Maximum=1.5
Calibration Minimum=0.5
Calibration Optimization Method= 1
WQ AD Non Conservative
WQ ULTIMATE=-1
WQ Max Comp Step=1HOUR
WQ Output Interval=15MIN
WQ Output Selected Increments= 0
WQ Output face flow=0
WQ Output face velocity=0
WQ Output face area=0
WQ Output face dispersion=0
WQ Output cell volume=0
WQ Output cell surface area=0
WQ Output cell continuity=0
WQ Output cumulative cell continuity=0
WQ Output face conc=0
WQ Output face dconc_dx=0
WQ Output face courant=0
WQ Output face peclet=0
WQ Output face adv mass=0
WQ Output face disp mass=0
WQ Output cell mass=0
WQ Output cell source sink temp=0
WQ Output nsm pathways=0
WQ Output nsm derived pathways=0
WQ Output MaxMinRange=-1
WQ Daily Max Min Mean=-1
WQ Daily Range=0
WQ Daily Time=0
WQ Create Restart=0
WQ Fixed Restart=0
WQ System Summary=0
WQ Write To DSS=0
WQ Use Fixed Temperature=0
Sorting and Armoring Iterations= 10
XS Update Threshold= 0.02
Bed Roughness Predictor= 0
Hydraulics Update Threshold= 0.02
Energy Slope Method= 1
Volume Change Method= 1
Sediment Retention Method= 0
XS Weighting Method= 0
Number of US Weighted Cross Sections= 1
Number of DS Weighted Cross Sections= 1
Upstream XS Weight=0
Main XS Weight=1
Downstream XS Weight=0
Number of DS XS's Weighted with US Boundary= 1
Upstream Boundary Weight= 1
Weight of XSs Associated with US Boundary= 0
Number of US XS's Weighted with DS Boundary= 1
Downstream Boundary Weight= 0.5
Weight of XSs Associated with DS Boundary= 0.5
Percentile Method= 0
Sediment Output Level= 3
Mass or Volume Output= 0
Output Increment Type= 1
Profile and TS Output Increment= 1
XS Output Flag= 0
XS Output Increment= 10
Write Gradation File= 0
Read Gradation Hotstart= 0
Write HDF5 File= 1
Write Binary Output= 1
Write DSS Sediment File= 0
SV Curve= 0
Specific Gage Flag= 0

--- RENICKCK.f01 (steady flow) ---

Flow Title=Flow
Program Version=5.07
Number of Profiles= 6
Profile Names=f1p,f10p,f4p,f2p,f02p,f1pplus
River Rch & RM=ALUMRN,Main            ,13094
     682     363     481     579     950    1010
River Rch & RM=ALUMRN,Main            ,11059
     799     428     565     679    1110    1180
River Rch & RM=ALUMRN,Main            ,9883
     965     521     686     821    1340    1430
River Rch & RM=ALUMRN,Main            ,6456
    1080     584     767     917    1490    1590
River Rch & RM=ALUMRN,Main            ,284
    1350     740     968    1160    1860    2000
River Rch & RM=KTCHNCK,Main            ,41842
     743     397     525     631    1030    1100
River Rch & RM=KTCHNCK,Main            ,37328
     832     446     589     707    1150    1230
River Rch & RM=KTCHNCK,Main            ,35092
     926     499     657     788    1280    1370
River Rch & RM=KTCHNCK,Main            ,33009
    1030     557     732     876    1420    1520
River Rch & RM=KTCHNCK,Main            ,28691
    1150     622     817     977    1580    1700
River Rch & RM=KTCHNCK,Main            ,21556
    1810    1000    1300    1550    2480    2680
River Rch & RM=KTCHNCK,Main            ,16488
    2900    1630    2110    2490    3930    4290
River Rch & RM=KTCHNCK,Main            ,10721
    3870    2200    2830    3340    5220    5730
River Rch & RM=KTCHNCKT1,Main            ,9111
     634     336     447     537     884     938
River Rch & RM=KTCHNCKT1,Main            ,6856
     715     381     504     606     994    1060
River Rch & RM=KTCHNCKT1,Main            ,2501
     856     459     606     727    1190    1270
River Rch & RM=MILLCK1,Main            ,44569
     546     288     383     462     764     808
River Rch & RM=MILLCK1,Main            ,42192
     668     355     471     567     931     988
River Rch & RM=MILLCK1,Main            ,40676
     926     498     657     787    1280    1370
River Rch & RM=MILLCK1,Main            ,39243
    1580     868    1130    1350    2160    2330
River Rch & RM=MILLCK1,Main            ,32901
    1760     973    1270    1510    2410    2610
River Rch & RM=MILLCK1,Main            ,26603
    1970    1090    1420    1690    2700    2920
River Rch & RM=MILLCK1,Main            ,16549
    2620    1470    1890    2240    3550    3870
River Rch & RM=MILLCK1,Main            ,5376
    3090    1740    2250    2650    4180    4570
River Rch & RM=MILLCK1T1,Main            ,2820
     564     298     397     478     789     835
River Rch & RM=RENICKCK,Main            ,22028
     617     327     434     523     861     913
River Rch & RM=RENICKCK,Main            ,19013
     695     370     490     589     967    1030
River Rch & RM=RENICKCK,Main            ,16528
     937     505     665     797    1300    1390
River Rch & RM=RENICKCK,Main            ,13874
    1040     565     742     888    1440    1540
River Rch & RM=RENICKCK,Main            ,9049
    1170     638     837    1000    1620    1740
River Rch & RM=SNAKERN,Main            ,20697
     463     243     324     392     650     685
River Rch & RM=SNAKERN,Main            ,20190
     763     408     539     648    1060    1130
River Rch & RM=SNAKERN,Main            ,19342
     852     457     603     724    1180    1260
River Rch & RM=SNAKERN,Main            ,16967
    1190     644     845    1010    1630    1750
River Rch & RM=SNAKERN,Main            ,11910
    1330     728     952    1140    1830    1970
River Rch & RM=SNAKERN,Main            ,6596
    1480     812    1060    1260    2030    2190
Boundary for River Rch & Prof#=ALUMRN,Main            , 1
Up Type= 0
Dn Type= 3
Dn Slope=0.008838
Boundary for River Rch & Prof#=ALUMRN,Main            , 2
Up Type= 0
Dn Type= 3
Dn Slope=0.008838
Boundary for River Rch & Prof#=ALUMRN,Main            , 3
Up Type= 0
Dn Type= 3
Dn Slope=0.008838
Boundary for River Rch & Prof#=ALUMRN,Main            , 4
Up Type= 0
Dn Type= 3
Dn Slope=0.008838
Boundary for River Rch & Prof#=ALUMRN,Main            , 5
Up Type= 0
Dn Type= 3
Dn Slope=0.008838
Boundary for River Rch & Prof#=ALUMRN,Main            , 6
Up Type= 0
Dn Type= 3
Dn Slope=0.008838
Boundary for River Rch & Prof#=KTCHNCK,Main            , 1
Up Type= 0
Dn Type= 3
Dn Slope=0.005801
Boundary for River Rch & Prof#=KTCHNCK,Main            , 2
Up Type= 0
Dn Type= 3
Dn Slope=0.005801
Boundary for River Rch & Prof#=KTCHNCK,Main            , 3
Up Type= 0
Dn Type= 3
Dn Slope=0.005801
Boundary for River Rch & Prof#=KTCHNCK,Main            , 4
Up Type= 0
Dn Type= 3
Dn Slope=0.005801
Boundary for River Rch & Prof#=KTCHNCK,Main            , 5
Up Type= 0
Dn Type= 3
Dn Slope=0.005801
Boundary for River Rch & Prof#=KTCHNCK,Main            , 6
Up Type= 0
Dn Type= 3
Dn Slope=0.005801
Boundary for River Rch & Prof#=KTCHNCKT1,Main            , 1
Up Type= 0
Dn Type= 3
Dn Slope=0.024951
Boundary for River Rch & Prof#=KTCHNCKT1,Main            , 2
Up Type= 0
Dn Type= 3
Dn Slope=0.024951
Boundary for River Rch & Prof#=KTCHNCKT1,Main            , 3
Up Type= 0
Dn Type= 3
Dn Slope=0.024951
Boundary for River Rch & Prof#=KTCHNCKT1,Main            , 4
Up Type= 0
Dn Type= 3
Dn Slope=0.024951
Boundary for River Rch & Prof#=KTCHNCKT1,Main            , 5
Up Type= 0
Dn Type= 3
Dn Slope=0.024951
Boundary for River Rch & Prof#=KTCHNCKT1,Main            , 6
Up Type= 0
Dn Type= 3
Dn Slope=0.024951
Boundary for River Rch & Prof#=MILLCK1,Main            , 1
Up Type= 0
Dn Type= 3
Dn Slope=0.000839
Boundary for River Rch & Prof#=MILLCK1,Main            , 2
Up Type= 0
Dn Type= 3
Dn Slope=0.000839
Boundary for River Rch & Prof#=MILLCK1,Main            , 3
Up Type= 0
Dn Type= 3
Dn Slope=0.000839
Boundary for River Rch & Prof#=MILLCK1,Main            , 4
Up Type= 0
Dn Type= 3
Dn Slope=0.000839
Boundary for River Rch & Prof#=MILLCK1,Main            , 5
Up Type= 0
Dn Type= 3
Dn Slope=0.000839
Boundary for River Rch & Prof#=MILLCK1,Main            , 6
Up Type= 0
Dn Type= 3
Dn Slope=0.000839
Boundary for River Rch & Prof#=MILLCK1T1,Main            , 1
Up Type= 0
Dn Type= 3
Dn Slope=0.000001
Boundary for River Rch & Prof#=MILLCK1T1,Main            , 2
Up Type= 0
Dn Type= 3
Dn Slope=0.000001
Boundary for River Rch & Prof#=MILLCK1T1,Main            , 3
Up Type= 0
Dn Type= 3
Dn Slope=0.000001
Boundary for River Rch & Prof#=MILLCK1T1,Main            , 4
Up Type= 0
Dn Type= 3
Dn Slope=0.000001
Boundary for River Rch & Prof#=MILLCK1T1,Main            , 5
Up Type= 0
Dn Type= 3
Dn Slope=0.000001
Boundary for River Rch & Prof#=MILLCK1T1,Main            , 6
Up Type= 0
Dn Type= 3
Dn Slope=0.000001
Boundary for River Rch & Prof#=RENICKCK,Main            , 1
Up Type= 0
Dn Type= 3
Dn Slope=0.003087
Boundary for River Rch & Prof#=RENICKCK,Main            , 2
Up Type= 0
Dn Type= 3
Dn Slope=0.003087
Boundary for River Rch & Prof#=RENICKCK,Main            , 3
Up Type= 0
Dn Type= 3
Dn Slope=0.003087
Boundary for River Rch & Prof#=RENICKCK,Main            , 4
Up Type= 0
Dn Type= 3
Dn Slope=0.003087
Boundary for River Rch & Prof#=RENICKCK,Main            , 5
Up Type= 0
Dn Type= 3
Dn Slope=0.003087
Boundary for River Rch & Prof#=RENICKCK,Main            , 6
Up Type= 0
Dn Type= 3
Dn Slope=0.003087
Boundary for River Rch & Prof#=SNAKERN,Main            , 1
Up Type= 0
Dn Type= 3
Dn Slope=0.008894
Boundary for River Rch & Prof#=SNAKERN,Main            , 2
Up Type= 0
Dn Type= 3
Dn Slope=0.008894
Boundary for River Rch & Prof#=SNAKERN,Main            , 3
Up Type= 0
Dn Type= 3
Dn Slope=0.008894
Boundary for River Rch & Prof#=SNAKERN,Main            , 4
Up Type= 0
Dn Type= 3
Dn Slope=0.008894
Boundary for River Rch & Prof#=SNAKERN,Main            , 5
Up Type= 0
Dn Type= 3
Dn Slope=0.008894
Boundary for River Rch & Prof#=SNAKERN,Main            , 6
Up Type= 0
Dn Type= 3
Dn Slope=0.008894
DSS Import GetInterval= 0
DSS Import GetPeak= 0
DSS Import FillOption= 0

--- RENICKCK.g01 (geometry) ---

Geom Title=Geometry
Program Version=5.07

River Reach=RENICKCK        ,Main
Reach XY= 30
2074022.32474136316066.9551402932074278.95283702315519.694095716
2075019.65214303315039.0861330482075367.92310002314501.371985376
2076143.26013201314157.8392078732076795.34347352313431.797680959
2077200.55165261312885.4434587062077526.07265511311752.110095456
2077220.94170368310878.0760823792077409.35996202310666.850126877
2077145.83194578310478.5040468722077211.48929477309832.839327708
2076810.67283919309501.7389400452076578.06109968307878.341924384
2076189.09337369 307620.860155882076352.58386037306969.322088882
2075905.23928261306418.2559337912076185.44738361 305594.81860429
2076038.57234928305528.1517428762076079.71826437304405.235353544
2076276.07253045304273.464291632 2075976.5934706303854.193476632
2076163.57242736303435.9643262182075982.84345812  303355.7561533
2075964.09316751302520.8601852952076809.40578136301776.068367794
2076755.39112562301509.1578123722076902.00566179301707.074411288
2077165.80762762301609.6786087162077190.32496703301167.423915789

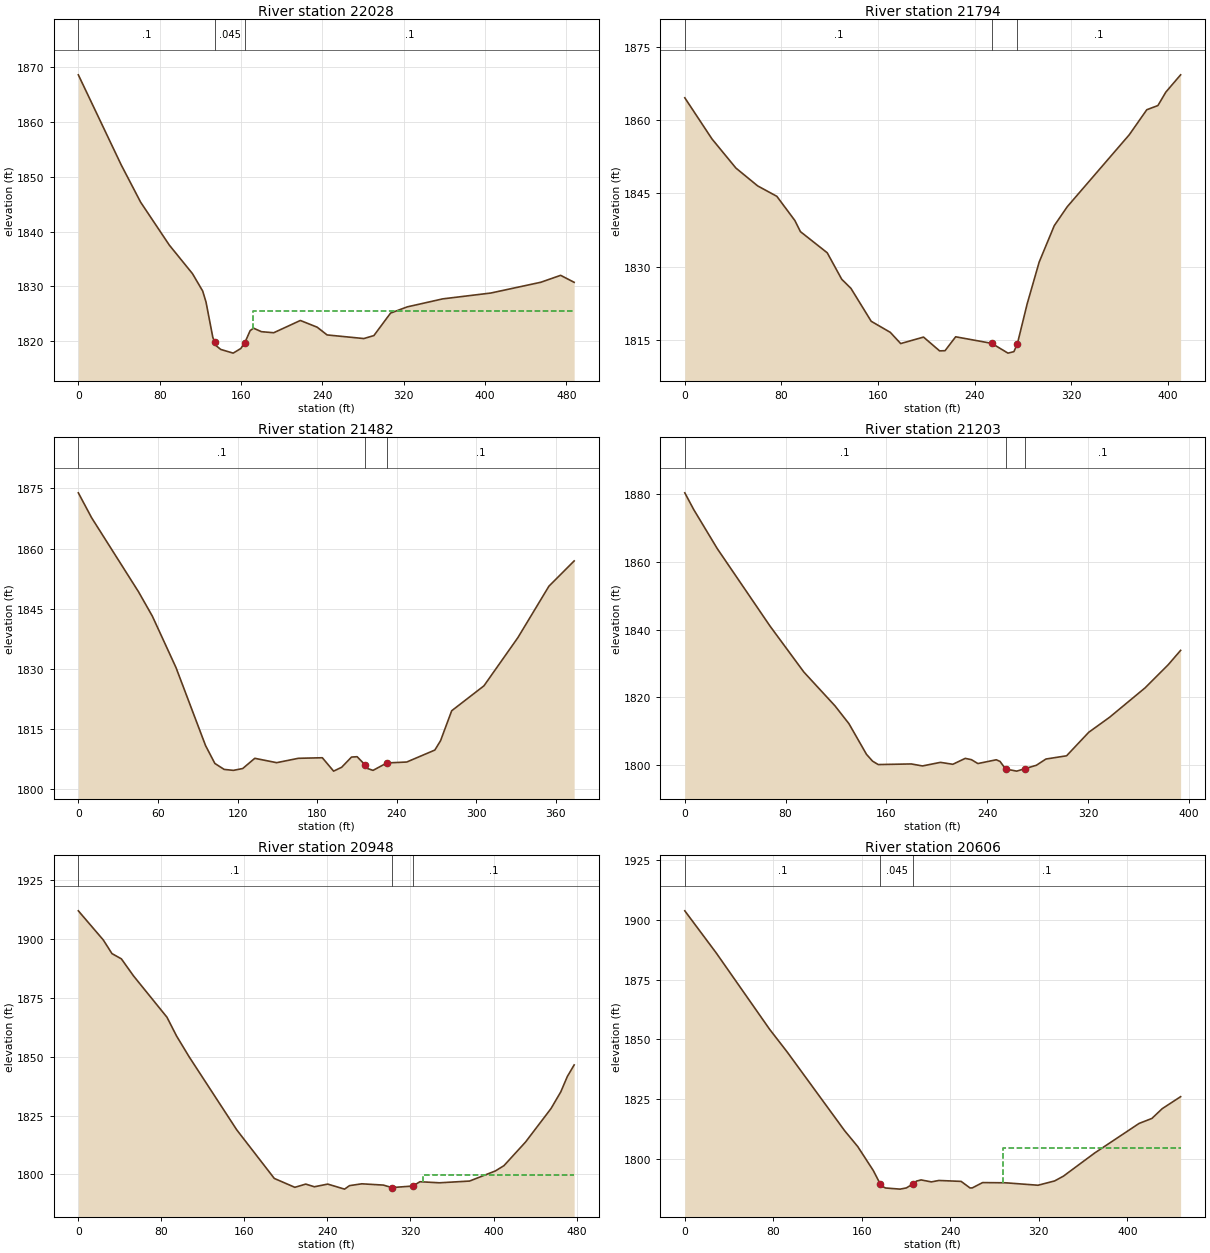
Type RM Length L Ch R = 1 ,22028   ,229.2,233.5,237.6
XS GIS Cut Line= 3
2074170.77752843 316082.63358663 2073993.6942212316049.647432134
2073686.40251294316035.758352295
#Sta/Elev= 30
       0  1868.5    42.2 1852.11    61.3 1845.33    89.5 1837.53   112.3 1832.33
   122.3 1829.18   125.6 1827.17   132.3 1820.74  134.281819.828   135.6 1819.22
   140.1 1818.55   152.3 1817.88   159.8 1818.72  163.75 1819.77     169 1821.97
   172.3 1822.42   180.1 1821.78   192.2 1821.59   218.4 1823.82   234.9  1822.6
   244.7 1821.19   280.8 1820.53   290.7 1821.07   307.1 1825.16   323.5 1826.29
   358.5 1827.75   405.7 1828.81   454.9 1830.77   474.4 1832.03   487.7 1830.76
#Mann= 3 ,-1 , 0
       0      .1       0  134.28    .045       0  163.75      .1       0
#XS Ineff= 2 , 0
                          171.48         1825.53
Permanent Ineff=
       F       F
Bank Sta=134.28,163.75
XS Rating Curve= 0 ,0
Exp/Cntr=0.3,0.1

Type RM Length L Ch R = 1 ,21794   ,311.1,312.7,311.6
XS GIS Cut Line= 3
2074223.15012711316005.3765233012074044.33093095315843.050076291
2073914.12252995315735.411183968
#Sta/Elev= 30
       0 1864.62    22.5 1856.18    42.3 1850.21    60.3 1846.55    76.2 1844.41
    91.1 1839.45    95.7 1837.17   117.9 1832.83   129.9  1827.4   137.5 1825.54
   154.3 1818.78   170.1 1816.51   178.7 1814.21   197.6 1815.54   210.9 1812.71
   215.4 1812.75   224.2  1815.6  254.031814.254   267.5 1812.25   272.4 1812.55
  275.281814.176   283.4 1822.37   293.3 1830.91   305.8 1838.39   316.6 1842.29
   367.9 1857.04   382.4 1862.17   391.6 1863.03   398.2  1865.8   410.4 1869.33
#Mann= 3 ,-1 , 0
       0      .1       0  254.03    .045       0  275.28      .1       0
Bank Sta=254.03,275.28
XS Rating Curve= 0 ,0
Exp/Cntr=0.3,0.1

Type RM Length L Ch R = 1 ,21482   ,278.1,278.4,277.7
XS GIS Cut Line= 3
2074432.35148036 315776.209986882074211.86537278 315595.65424563
2074144.15717486315538.362693548
#Sta/Elev= 30
       0 1873.91      10  1867.7    45.4 1849.19    55.8 1843.12    73.6  1830.3
    95.9 1810.81   102.9 1806.36   109.9 1804.87   116.9 1804.63   123.9 1805.09
     133 1807.64   149.5 1806.55   165.8 1807.64   183.9 1807.78   192.4 1804.44
   198.5 1805.41   205.9 1807.95   210.1 1808.04  216.191805.983   217.8 1805.11
   222.1 1804.63  232.571806.485   247.5 1806.71   268.7  1809.7     273 1812.03
   281.4 1819.51   305.7 1825.73   331.3 1837.77   354.7 1850.61   373.7 1856.91
#Mann= 3 ,-1 , 0
       0      .1       0  216.19    .045       0  232.57      .1       0
Bank Sta=216.19,232.57
XS Rating Curve= 0 ,0
Exp/Cntr=0.3,0.1

Type RM Length L Ch R = 1 ,21203   ,253.5,255.7,257.1
XS GIS Cut Line= 2
2074611.17100459315623.432077214 2074317.7683762315361.279386297
#Sta/Elev= 30
       0 1880.45     7.1  1875.5    25.7 1864.01    67.6 1841.11    94.5 1827.51
   119.2 1817.53   130.3 1812.25   144.2 1803.21     149  1801.2   153.5 1800.19
   179.8 1800.37   188.6 1799.78   202.9 1800.84   212.7 1800.27   222.6 1802.02
   227.5 1801.63   232.6 1800.49   247.2  1801.6   250.2 1801.11   254.6 1798.88
   263.4 1798.25   269.7 1798.94     279 1799.98   286.6 1801.82     303 1802.78
   320.6 1809.73   337.1 1814.15   365.4 1822.88   383.6 1829.65   393.5 1833.92
#Mann= 3 , 0 , 0
       0      .1       0   254.6    .045       0   269.7      .1       0
Bank Sta=254.6,269.7
XS Rating Curve= 0 ,0
Exp/Cntr=0.3,0.1

Type RM Length L Ch R = 1 ,20948   ,340.7,341.7,340.1
XS GIS Cut Line= 2
2074778.70577452315510.5848619642074486.17092651315132.980630293
#Sta/Elev= 30
       0 1912.07    24.1 1899.65    32.4 1893.88    41.5 1891.63    53.1 1884.43
    85.4 1866.81    94.6 1858.86   106.8 1849.95   152.7 1818.86   188.8 1798.24
   208.6 1794.46   219.1 1795.83   227.4 1794.69   240.3 1795.83   256.5 1793.69
   261.3 1795.18   273.1 1795.95   293.9 1795.41  302.111794.346  322.411795.017
   329.1 1796.84   347.9 1796.38   376.9 1797.12   401.8 1801.42   410.1 1803.69
   430.8 1813.69   455.4 1827.96   464.8 1835.05   471.1 1841.57   477.7 1846.52
#Mann= 3 ,-1 , 0
       0      .1       0  302.11    .045       0  322.41      .1       0
#XS Ineff= 2 , 0
                           332.2         1799.52
Permanent Ineff=
       F       F
Bank Sta=302.11,322.41
XS Rating Curve= 0 ,0
Exp/Cntr=0.3,0.1

Type RM Length L Ch R = 1 ,20606   ,306.6,303.3,297.8
XS GIS Cut Line= 2
 2074996.5875566315288.3625373842074737.03919119314922.911168545
#Sta/Elev= 30
       0 1903.88    28.5 1886.17    76.7 1854.21    92.6 1844.69   144.5 1811.71
   156.3 1805.09   170.4 1795.02  176.681789.378   177.6 1788.62   181.4 1787.71
   194.6 1787.23   200.3 1787.74  206.131789.365   209.5  1790.6   213.6 1791.09
   222.9 1790.26   229.7 1790.86   249.8 1790.47   257.8 1787.73   259.8 1787.73
   269.2 1789.97     290 1789.88   319.3 1788.86   334.3 1790.66   342.2 1792.65
   370.5 1802.37   410.7 1814.78   422.2 1816.85   431.6 1820.97   448.2 1825.98
#Mann= 3 ,-1 , 0
       0      .1       0  176.68    .045       0  206.13      .1       0
#XS Ineff= 2 , 0
                          287.21         1804.62
Permanent Ineff=
       F       F
Bank Sta=176.68,206.13
XS Rating Curve= 0 ,0
Exp/Cntr=0.3,0.1

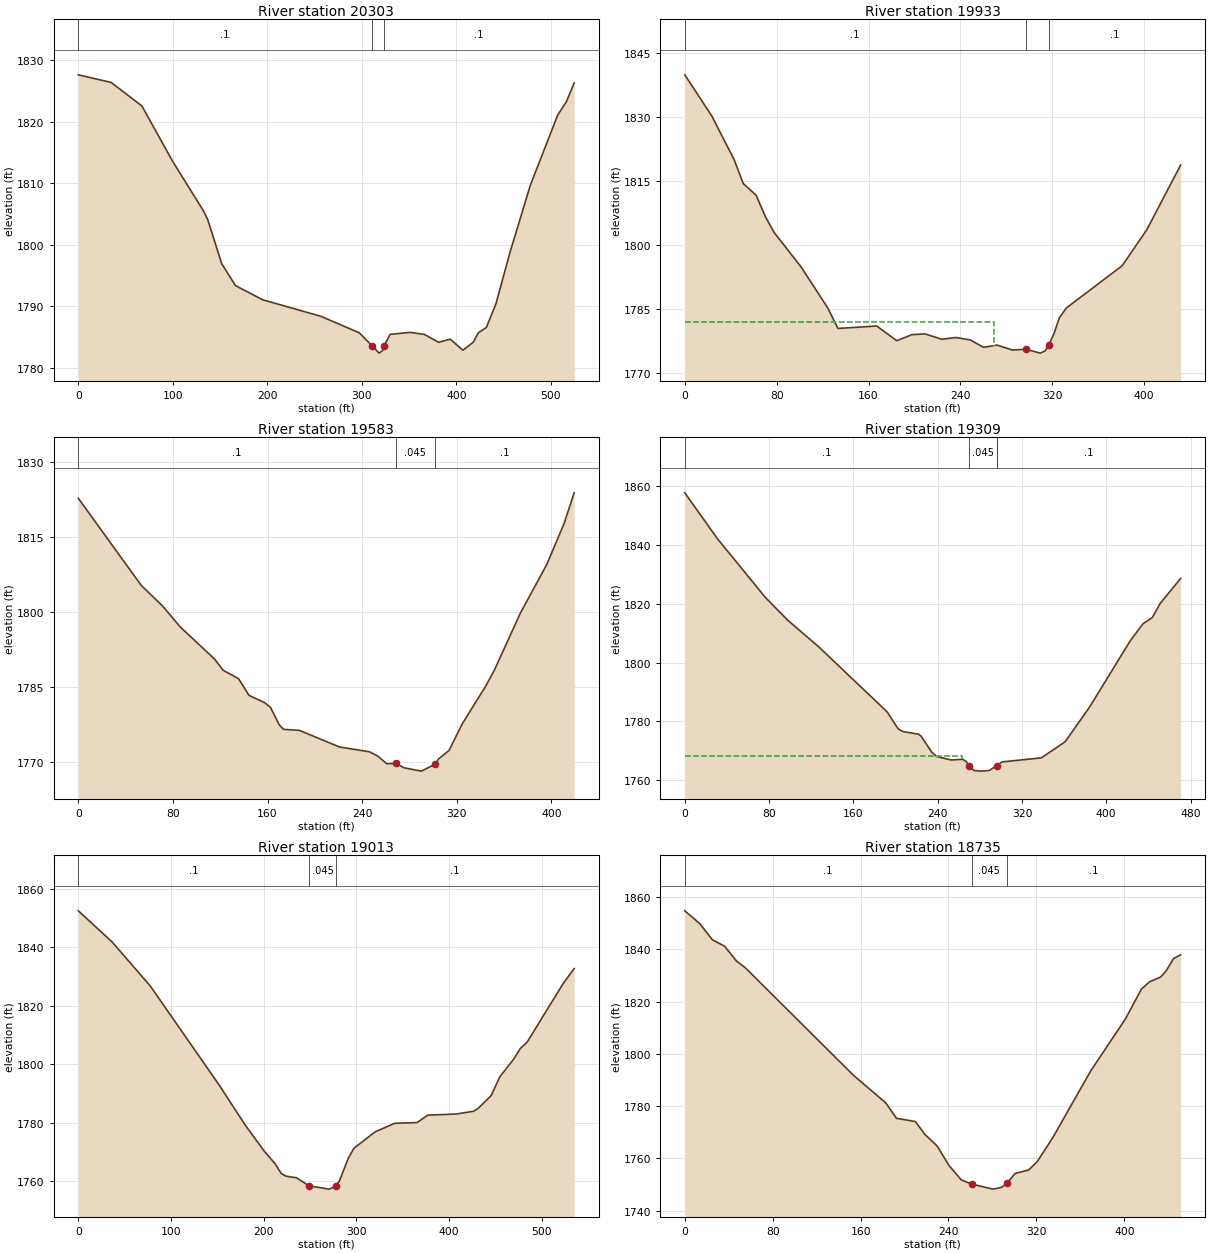
Type RM Length L Ch R = 1 ,20303   ,365,369.9,372.2
XS GIS Cut Line= 3
2075254.40036118 315120.828095542075033.91425359314921.175279632
2074857.69872677314777.945907295
#Sta/Elev= 30
       0 1827.66    34.7 1826.42    67.2  1822.6    99.7 1813.61   132.5 1805.49
   136.9 1804.12   151.6 1796.95   166.2 1793.37     195 1791.06   256.4 1788.38
   297.2 1785.69   310.4 1783.62   318.2 1782.38   321.7 1782.78   323.6 1783.61
   329.8 1785.43   350.8 1785.76   365.9 1785.43   381.1 1784.15   393.5 1784.64
   406.8 1782.86   417.9 1784.17   423.1 1785.69   431.6 1786.54   441.8 1790.43
   456.9 1798.92   478.1 1809.67   507.1 1821.11   516.4 1823.32   524.5 1826.33
#Mann= 3 , 0 , 0
       0      .1       0   310.4    .045       0   323.6      .1       0
Bank Sta=310.4,323.6
XS Rating Curve= 0 ,0
Exp/Cntr=0.3,0.1

Type RM Length L Ch R = 1 ,19933   ,346.8,349.6,351
XS GIS Cut Line= 2
2075405.44172576314904.6822023842075175.40708086314539.230833545
#Sta/Elev= 30
       0 1839.87    23.7 1830.13    43.1 1819.89    50.9 1814.36    62.1 1811.62
    70.3 1806.52      78 1802.81   101.3 1794.77   124.5 1785.17   133.4 1780.35
   167.2 1780.92   184.6 1777.47   197.7 1778.89   209.2 1779.07   223.9 1777.81
   235.8 1778.23   248.6 1777.66   260.2 1775.92   271.9 1776.45   285.7 1775.26
  296.82 1775.49   309.5 1774.56   313.9 1775.09  316.841776.428   321.4 1779.04
   326.1 1782.81   332.4 1785.18   380.9 1795.07   402.3 1803.49   431.8 1818.69
#Mann= 3 ,-1 , 0
       0      .1       0  296.82    .045       0  316.84      .1       0
#XS Ineff= 2 , 0
           269.1 1781.87
Permanent Ineff=
       F       F
Bank Sta=296.82,316.84
XS Rating Curve= 0 ,0
Exp/Cntr=0.3,0.1

Type RM Length L Ch R = 1 ,19583   ,272.9,274.2,273.7
XS GIS Cut Line= 2
2075636.97768003 314709.442107292075454.68604985314331.837875634
#Sta/Elev= 30
       0 1822.75    53.2 1805.35    71.5 1801.16      86 1797.09   115.2 1790.63
   122.5 1788.38   135.5 1786.72   144.3 1783.38   157.6 1781.91   162.5 1780.97
   169.8 1777.55   173.5 1776.59   187.1 1776.37   220.8 1773.07   246.1 1772.11
   253.1 1771.27   260.8 1769.72  268.621769.793   275.5  1768.9     290 1768.24
  301.37 1769.57   304.6 1770.66   313.5 1772.38   324.5 1777.62   344.7  1785.3
     352  1788.5   373.8 1799.81     396 1809.45   410.7 1817.65   419.3 1823.84
#Mann= 3 ,-1 , 0
       0      .1       0  268.62    .045       0  301.37      .1       0
Bank Sta=268.62,301.37
XS Rating Curve= 0 ,0
Exp/Cntr=0.3,0.1

Type RM Length L Ch R = 1 ,19309   ,300.5,296.2,290.5
XS GIS Cut Line= 2
2075872.43783903314603.105049625 2075678.2102091314174.502560377
#Sta/Elev= 30
       0 1857.83      31  1842.2    76.4 1822.25    97.8 1814.43   126.8  1805.5
   192.1 1783.23   202.4  1777.5     207 1776.54   221.9 1775.65   224.4 1774.93
   234.3 1769.56   239.2 1768.03   252.9 1766.86   263.7  1767.1   267.3 1766.29
  269.611764.955   274.5 1763.27   281.7 1763.07   288.9 1763.28   296.1 1764.97
   296.2 1765.02   301.2 1766.21   338.4 1767.59   360.9 1773.04     384 1784.77
   422.6 1807.34     435  1813.3   443.8 1815.38     451 1820.08   470.6 1828.68
#Mann= 4 ,-1 , 0
       0      .1       0  269.61    .045       0   296.1    .045       0
   296.2      .1       0
#XS Ineff= 2 , 0
          262.94 1768.14
Permanent Ineff=
       F       F
Bank Sta=269.61,296.1
XS Rating Curve= 0 ,0
Exp/Cntr=0.3,0.1

Type RM Length L Ch R = 1 ,19013   ,281.3,278,270.3
XS GIS Cut Line= 3
2076207.72424194314425.153633878 2075984.1997546314195.118988961
2075835.54519626314041.039244622
#Sta/Elev= 30
       0 1852.56    36.4 1841.92    77.6 1826.82   151.9 1792.89   179.7 1779.33
   200.6 1770.21   212.2 1765.96   218.9  1762.6   223.8 1761.69   235.4 1761.12
  248.741758.368   270.7 1757.24   278.21758.368   281.8 1760.18   291.1 1767.76
   297.2 1771.22   320.1 1776.85   341.4  1779.8   365.3 1780.03   376.9 1782.57
   407.6 1782.97   426.5 1783.92   431.2  1784.9   445.4 1789.33   454.8  1795.8
   469.8 1801.84   476.7  1805.4   484.2 1807.65   523.1 1827.73   534.8 1832.78
#Mann= 3 ,-1 , 0
       0      .1       0  248.74    .045       0   278.2      .1       0
Bank Sta=248.74,278.2
XS Rating Curve= 0 ,0
Exp/Cntr=0.3,0.1

Type RM Length L Ch R = 1 ,18735   ,248.2,248.9,250.1
XS GIS Cut Line= 2
2076451.86482978314158.2266742892076046.04871228313960.744129628
#Sta/Elev= 30
       0 1854.76    13.6 1849.88    25.2 1843.64    36.2 1841.23    47.1 1835.53
    55.3 1832.87   153.4 1791.84   182.9 1781.24   192.7 1775.31   209.9 1774.09
   218.6 1769.12   229.7 1764.72   240.5 1757.27   251.6 1751.76  261.091750.143
   280.6 1748.21   288.4 1748.91   293.3 1750.52   300.7 1754.22     313 1755.54
   320.8 1758.75   335.4 1768.24   369.4 1793.43   401.1 1813.39   415.6 1824.78
   422.9 1827.56   433.2 1829.43   438.2 1831.82   444.8 1836.48   451.3 1837.92
#Mann= 3 , 0 , 0
       0      .1       0  261.09    .045       0   293.3      .1       0
Bank Sta=261.09,293.3
XS Rating Curve= 0 ,0
Exp/Cntr=0.3,0.1

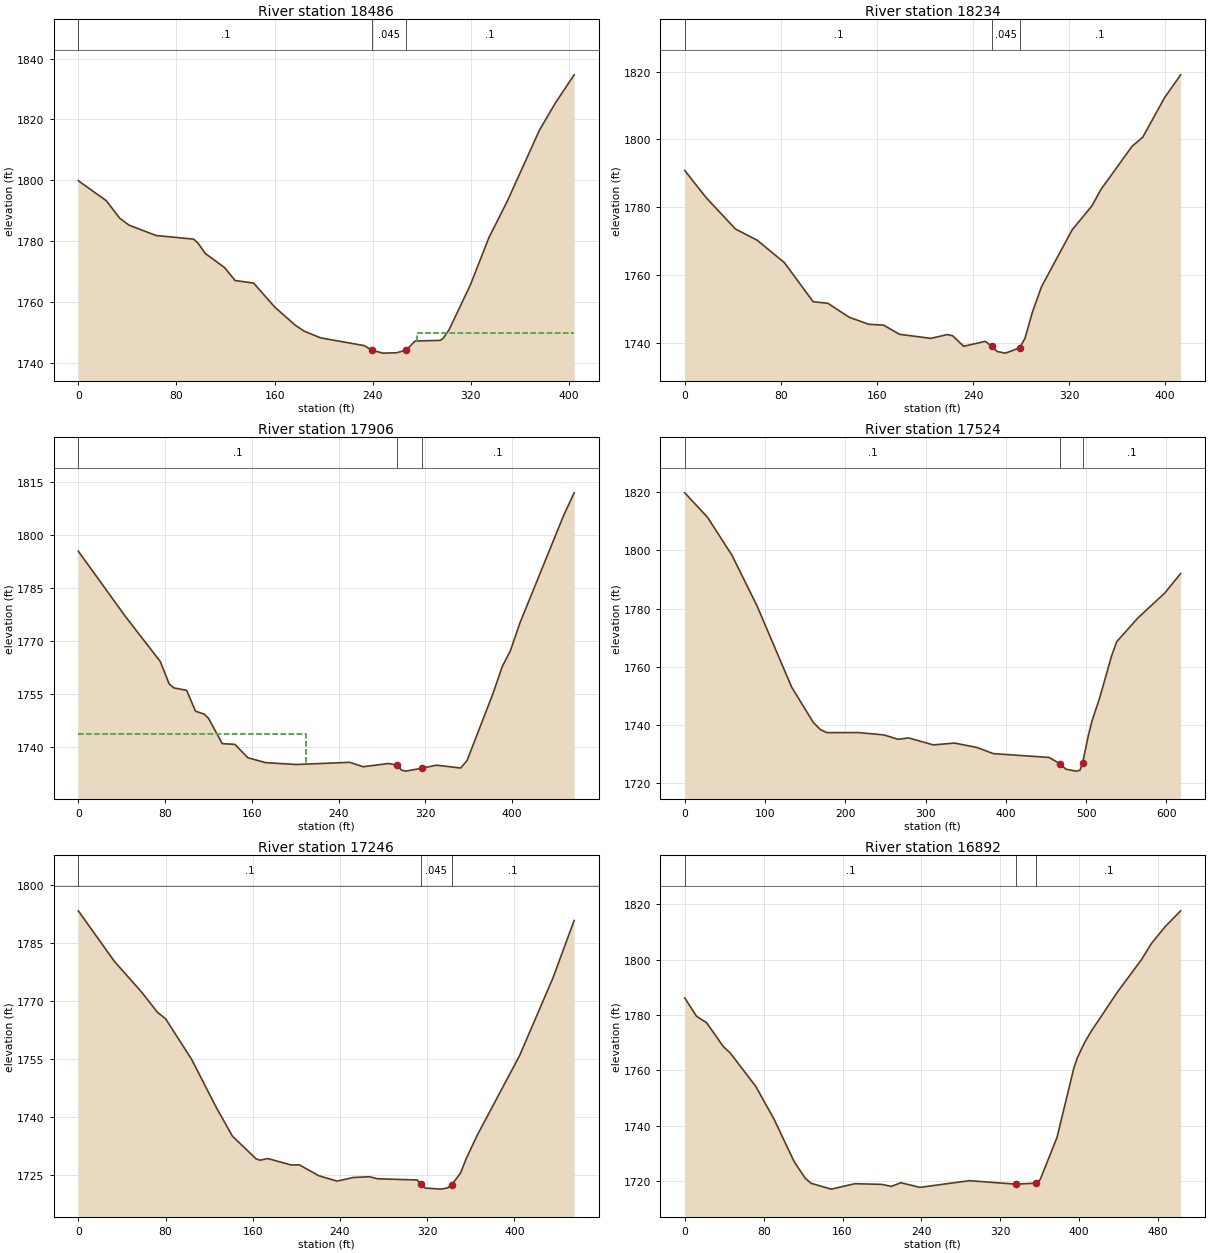
Type RM Length L Ch R = 1 ,18486   ,249.5,252.3,256.3
XS GIS Cut Line= 2
2076557.11658779313950.9784011242076204.46899912313753.495856464
#Sta/Elev= 30
       0 1799.85    22.6 1793.36    33.8  1787.5    41.4 1785.24    63.4 1781.84
      94 1780.65    97.5 1779.38   103.6  1775.9   119.2 1771.31   127.8 1767.05
   142.9  1766.2   160.1 1758.32   176.7  1752.4   184.2 1750.37   197.6 1748.18
   233.1 1745.64  239.641744.107   248.2 1743.17   259.4 1743.28  267.281744.172
   274.5 1747.15   295.1 1747.37   297.5 1748.07   302.3 1750.91   319.6 1765.61
   334.7 1781.14   349.7 1793.13     376 1816.56   389.1 1825.55   404.2 1834.68
#Mann= 3 ,-1 , 0
       0      .1       0  239.64    .045       0  267.28      .1       0
#XS Ineff= 2 , 0
                          275.89         1749.92
Permanent Ineff=
       F       F
Bank Sta=239.64,267.28
XS Rating Curve= 0 ,0
Exp/Cntr=0.3,0.1

Type RM Length L Ch R = 1 ,18234   ,325,327.8,329.3
XS GIS Cut Line= 2
2076699.26066044313824.0252429542076399.78127253313539.737097621
#Sta/Elev= 30
       0 1790.83    17.8 1782.82    42.2 1773.57    60.3 1770.26    82.9 1763.66
   106.9 1752.12   119.1 1751.66     137 1747.52   153.3 1745.46   165.5 1745.22
   178.8 1742.51     205  1741.3   218.6 1742.43   223.1 1742.06   232.2 1738.97
   250.3 1740.42  255.621738.946   260.1 1737.42     267 1736.95  278.791738.483
   283.3 1741.33   289.4 1748.96   297.2 1756.66   322.6 1773.34     339 1780.38
   346.6 1785.27   372.4 1797.95   381.4 1800.68   399.5 1812.31   412.9 1819.07
#Mann= 3 ,-1 , 0
       0      .1       0  255.62    .045       0  278.79      .1       0
Bank Sta=255.62,278.79
XS Rating Curve= 0 ,0
Exp/Cntr=0.3,0.1

Type RM Length L Ch R = 1 ,17906   ,380.5,382.2,376.3
XS GIS Cut Line= 2
2076943.40124828313695.987113208 2076676.4742887313324.893367216
#Sta/Elev= 30
       0 1795.48    43.3 1777.02    75.6 1764.17    83.7 1757.86      88 1756.72
    99.9    1756     108  1750.1   116.2 1749.24   120.1 1748.04   132.7 1740.89
   144.4 1740.68   156.2  1736.9   172.6  1735.5   200.9 1734.97   250.2 1735.59
   262.6 1734.33   285.8 1735.25  293.861734.817   297.9 1733.39   301.9 1733.09
  316.721733.909   330.1 1734.78   352.5 1733.97   358.4 1736.12   381.9 1754.79
   390.9 1762.82   398.3 1767.22     407 1775.05   447.4 1805.64   457.1 1812.05
#Mann= 3 ,-1 , 0
       0      .1       0  293.86    .045       0  316.72      .1       0
#XS Ineff= 2 , 0
          209.68 1743.49
Permanent Ineff=
       F       F
Bank Sta=293.86,316.72
XS Rating Curve= 0 ,0
Exp/Cntr=0.3,0.1

Type RM Length L Ch R = 1 ,17524   ,281.5,277.3,273
XS GIS Cut Line= 2
2077339.45163727313476.8031683712076878.29704776313065.561864883
#Sta/Elev= 30
       0 1819.82    28.4 1811.37    58.7 1798.37    89.9 1780.99   133.3 1752.88
   160.2 1740.78     169 1738.34     177 1737.29   216.4 1737.31   248.2  1736.5
   265.7    1735   278.9 1735.47   309.7 1733.06   336.1  1733.7   364.3 1732.17
   384.4 1730.07     454 1728.75   467.51726.595   474.9 1724.71   487.6 1724.04
   492.5 1724.35  495.681726.759   503.1 1736.56   507.5 1741.34   517.1 1749.31
   531.9 1763.72   538.3 1768.61   564.7 1776.77     598 1785.29   617.9 1792.04
#Mann= 3 ,-1 , 0
       0      .1       0   467.5    .045       0  495.68      .1       0
Bank Sta=467.5,495.68
XS Rating Curve= 0 ,0
Exp/Cntr=0.3,0.1

Type RM Length L Ch R = 1 ,17246   ,355.6,353.8,351.6
XS GIS Cut Line= 2
2077466.40479544313092.6884510522077052.99322069312902.801363632
#Sta/Elev= 30
       0 1793.36      33 1780.34    58.3 1772.29    72.7 1767.12      80 1765.51
   103.9 1755.03   126.1 1742.82   141.3 1735.19     163 1729.32   166.6 1728.95
   173.8 1729.38   195.4 1727.71   202.7 1727.76   220.8 1724.92   237.4 1723.55
   252.3 1724.49   267.1 1724.68   274.6 1724.15     311 1723.84   314.1 1722.68
   318.3 1721.76   332.7 1721.48   338.9 1721.82   342.7 1722.64   350.7 1725.64
     356 1729.45   366.1 1735.46   404.9 1756.01   435.4    1776   454.9 1790.87
#Mann= 3 , 0 , 0
       0      .1       0   314.1    .045       0   342.7      .1       0
Bank Sta=314.1,342.7
XS Rating Curve= 0 ,0
Exp/Cntr=0.3,0.1

Type RM Length L Ch R = 1 ,16892   ,365.8,364.8,363.1
XS GIS Cut Line= 2
2077608.54886812312718.3394622062077125.69287845312577.280361131
#Sta/Elev= 30
       0 1786.15    11.9 1779.54    22.1 1777.21    39.2 1768.55    46.1 1766.28
      72 1754.22    90.5 1742.39     111 1726.99   122.2 1721.05   128.1  1719.2
   148.6  1717.1   172.5 1719.06   199.9 1718.82   209.5 1718.07   219.1 1719.41
   238.6 1717.74   288.7 1720.15  336.26 1718.88  356.311719.276   360.5 1720.53
   377.6 1735.76   394.7 1760.87   398.1 1764.43   404.9 1769.59   411.8 1773.85
   439.1 1788.39   463.4 1800.06   473.3  1805.8   487.2 1811.86     503 1817.63
#Mann= 3 ,-1 , 0
       0      .1       0  336.26    .045       0  356.31      .1       0
Bank Sta=336.26,356.31
XS Rating Curve= 0 ,0
Exp/Cntr=0.3,0.1

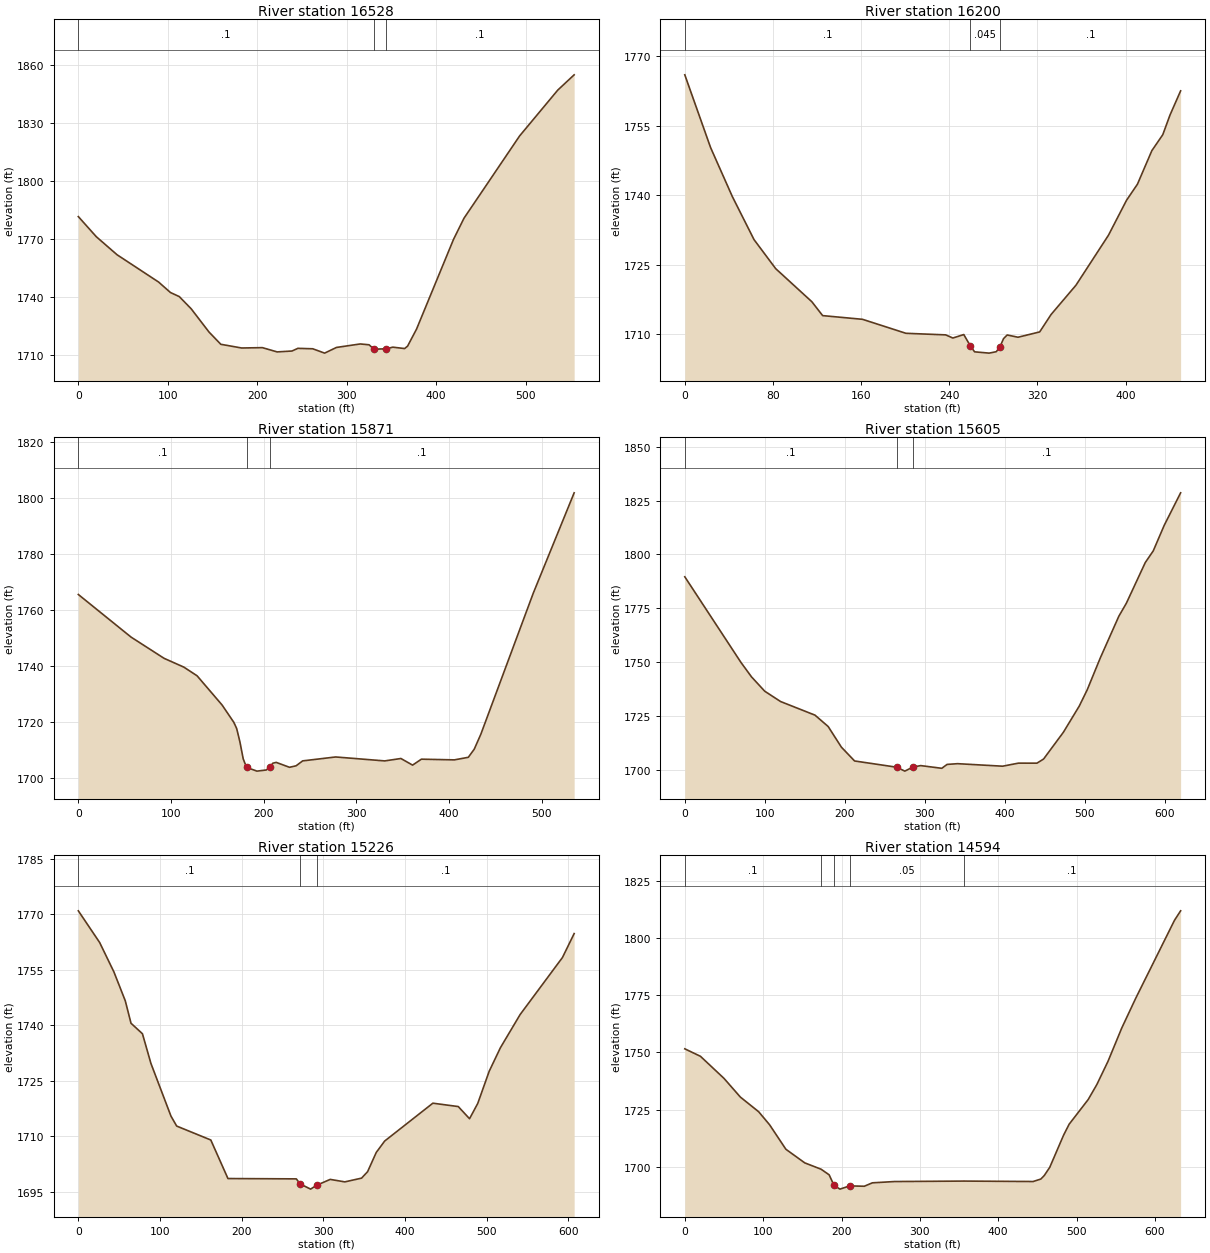
Type RM Length L Ch R = 1 ,16528   ,330.1,327.8,324.8
XS GIS Cut Line= 2
2077725.30224353312328.4741002172077176.69113603312248.613039464
#Sta/Elev= 30
       0 1781.71    20.1 1771.28    43.3 1761.94    89.7 1747.81     103 1742.38
   112.9 1740.25   126.2 1733.93   146.1 1721.91   159.3 1715.55   182.6 1713.63
   205.8 1713.81   222.3  1711.6   238.9 1712.06   245.5 1713.45   262.1 1713.22
   275.4 1710.97   288.6 1713.91   315.2 1715.72   325.1 1715.29   330.5 1713.02
   344.3  1713.2   351.6 1714.06   364.9 1713.34   368.2 1714.63   378.2 1723.45
   419.5 1769.89   431.2 1780.85   493.4 1823.49   536.1 1847.26   554.4 1855.16
#Mann= 3 , 0 , 0
       0      .1       0   330.5    .045       0   344.3      .1       0
Bank Sta=330.5,344.3
XS Rating Curve= 0 ,0
Exp/Cntr=0.3,0.1

Type RM Length L Ch R = 1 ,16200   ,331.8,328.9,319.6
XS GIS Cut Line= 2
2077728.77434945311983.8560230432077279.12170544311967.362945795
#Sta/Elev= 30
       0 1765.96    23.4 1750.26    43.1  1739.7    62.8 1730.39    82.5 1724.11
   115.3 1716.97   125.1 1713.97   161.3 1713.17   200.7 1710.15   236.8 1709.81
   243.3 1709.13   253.2 1709.88  259.03 1707.48     263 1706.15   276.2 1705.87
   282.7 1706.18     286 1707.23   289.3    1709   292.6 1709.79   302.4  1709.3
   322.1 1710.45   332.4  1714.2     355 1720.53   384.5 1731.32   400.9 1738.87
   410.8 1742.34   423.9 1749.59   433.8 1753.03   440.3 1757.24     450  1762.5
#Mann= 3 , 0 , 0
       0      .1       0  259.03    .045       0     286      .1       0
Bank Sta=259.03,286
XS Rating Curve= 0 ,0
Exp/Cntr=0.3,0.1

Type RM Length L Ch R = 1 ,15871   ,263.4,266.3,269.2
XS GIS Cut Line= 2
2077675.82301179311594.0989285412077182.76756743 311801.56439288
#Sta/Elev= 30
       0 1765.63    56.9  1750.4    92.5 1742.82   113.8 1739.68   128.1 1736.58
   155.1 1726.13   167.7 1719.97   170.8 1717.76   174.3 1712.99   177.9 1706.87
   181.5 1703.84   192.7 1702.51   202.8 1702.92   206.4 1703.93   209.9 1705.35
   213.5 1705.63   227.8 1703.88   234.9 1704.41     242 1706.17   277.6 1707.57
   330.5 1706.16     348 1707.02   360.6 1704.66   370.1 1706.78   405.7 1706.53
   420.7 1707.45   427.1 1710.34   434.2 1715.67   490.8 1766.11   534.9 1801.96
#Mann= 3 , 0 , 0
       0      .1       0   181.5    .045       0   206.4      .1       0
Bank Sta=181.5,206.4
XS Rating Curve= 0 ,0
Exp/Cntr=0.3,0.1

Type RM Length L Ch R = 1 ,15605   ,379.4,378.9,374.8
XS GIS Cut Line= 2
2077676.69112027311389.2377897052077061.23992336311461.286530122
#Sta/Elev= 30
       0 1789.58    70.2 1749.79    83.4 1743.07    99.9 1736.42   119.7 1731.62
   162.7  1725.3   179.2 1720.01   195.7 1710.43   212.2    1704  264.921701.096
     275 1699.28  285.011701.145   294.8 1701.85   321.2 1700.59   327.8  1702.4
     341 1702.74   397.2 1701.57     417 1702.99   440.1 1702.98   448.4 1704.89
   473.2 1717.36     493  1729.5   502.9 1737.01   519.3 1751.88   542.5 1771.27
   551.9 1777.31   575.5 1796.19   585.5 1801.63   599.2  1813.5   619.7  1828.6
#Mann= 3 ,-1 , 0
       0      .1       0  264.92    .045       0  285.01      .1       0
Bank Sta=264.92,285.01
XS Rating Curve= 0 ,0
Exp/Cntr=0.3,0.1

Type RM Length L Ch R = 1 ,15226   ,627.7,631.8,628.1
XS GIS Cut Line= 3
2077661.06615153310983.8560545442077280.85792243311121.876775876
2077088.14964643311184.376978964
#Sta/Elev= 30
       0  1770.9    26.1 1762.34    43.6 1754.37    57.5 1746.57    64.5 1740.51
    78.5 1737.67    88.9 1729.64   113.4 1715.42   120.4 1712.72   162.2 1708.95
   183.2 1698.53   266.9 1698.44  271.691697.064   284.4 1695.67  291.741696.708
   308.4  1698.3   326.3 1697.63   346.8 1698.64   354.2 1700.39   364.8 1705.59
   375.1 1708.67   434.1  1718.9   465.2 1717.99     479  1714.7   489.1 1718.86
   503.1 1727.55   516.9 1733.93     541 1742.88   592.8 1758.29   607.1 1764.75
#Mann= 3 ,-1 , 0
       0      .1       0  271.69    .045       0  291.74      .1       0
Bank Sta=271.69,291.74
XS Rating Curve= 0 ,0
Exp/Cntr=0.3,0.1

Type RM Length L Ch R = 1 ,14594   ,339.4,342.4,343.6
XS GIS Cut Line= 3
2077598.34908536310600.1753914652077366.14416918310676.130292043
2077005.90112329310821.529607549
#Sta/Elev= 30
       0 1751.59      20 1748.32    50.1 1738.66    70.9 1730.53    94.3 1724.12
   108.3  1718.4     129 1707.75   153.1  1701.8   173.9 1699.04   184.2 1696.59
   190.4 1692.02     198 1690.34  210.511691.751   229.1  1691.6   239.4 1693.09
   267.6 1693.65   356.1 1693.85   444.5 1693.66   454.4 1694.74   458.7 1696.25
   465.8 1699.87   483.4 1713.87   490.5 1718.66   514.9 1729.48   525.9 1736.01
   540.1 1746.12   557.7 1760.69   575.3 1773.52     625 1807.71   632.8 1811.83
#Mann= 5 ,-1 , 0
       0      .1       0   173.9     .05       0   190.4    .045       0
  210.51     .05       0   356.1      .1       0
Bank Sta=190.4,210.51
XS Rating Curve= 0 ,0
Exp/Cntr=0.3,0.1