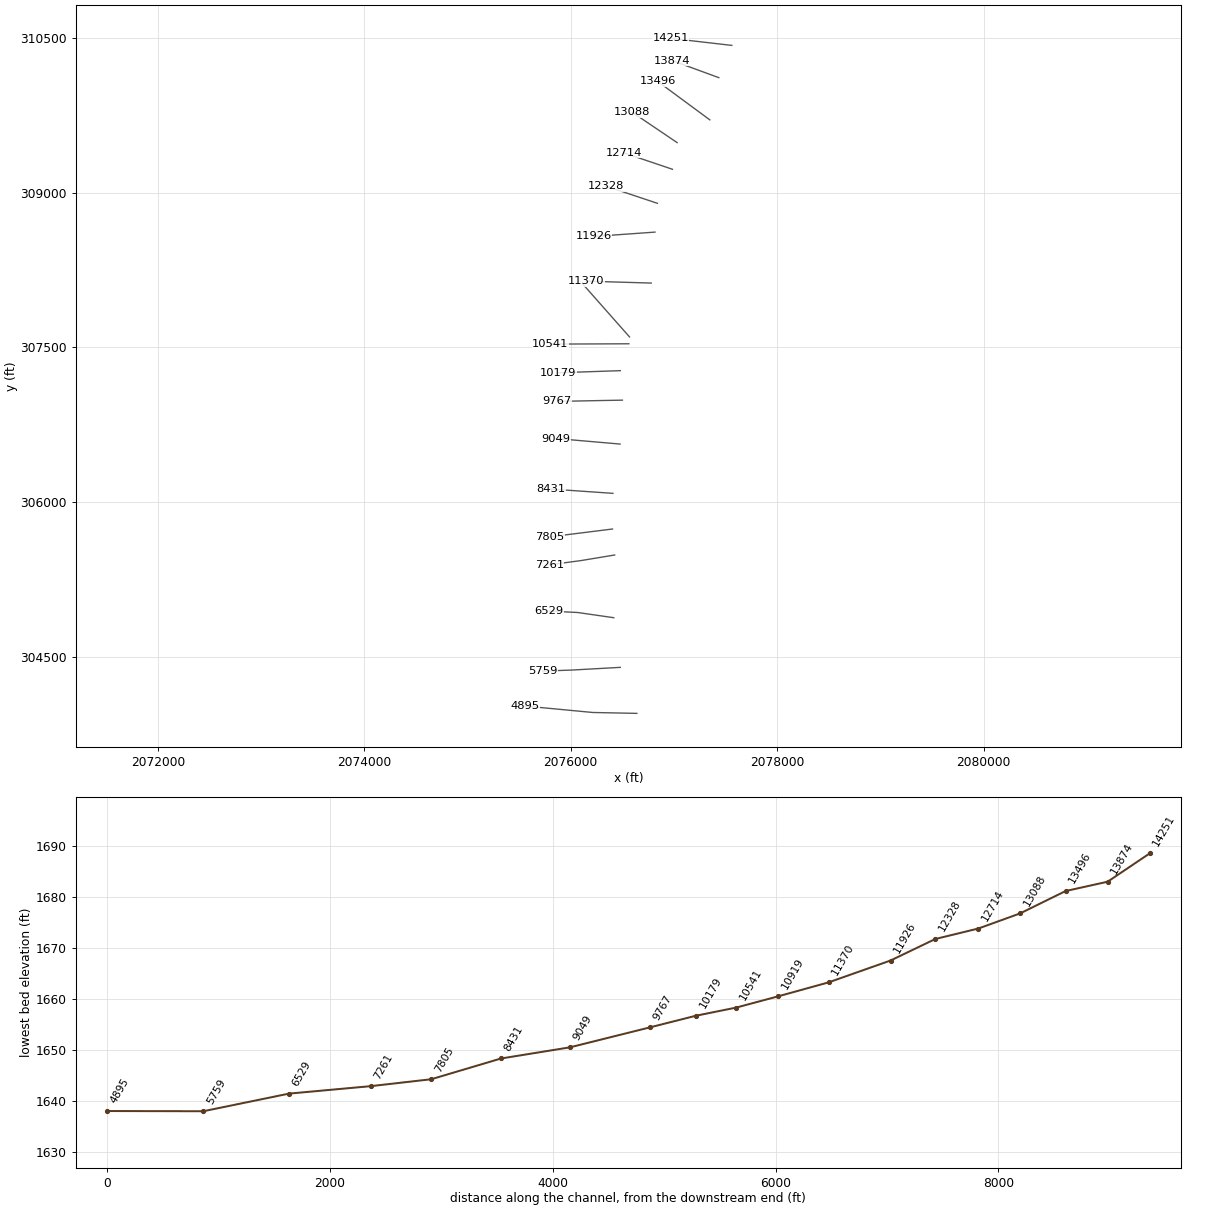
HEC-RAS study RENICKCK.prj: RENICKCK

--- RENICKCK.g01 (geometry) --- (continued)

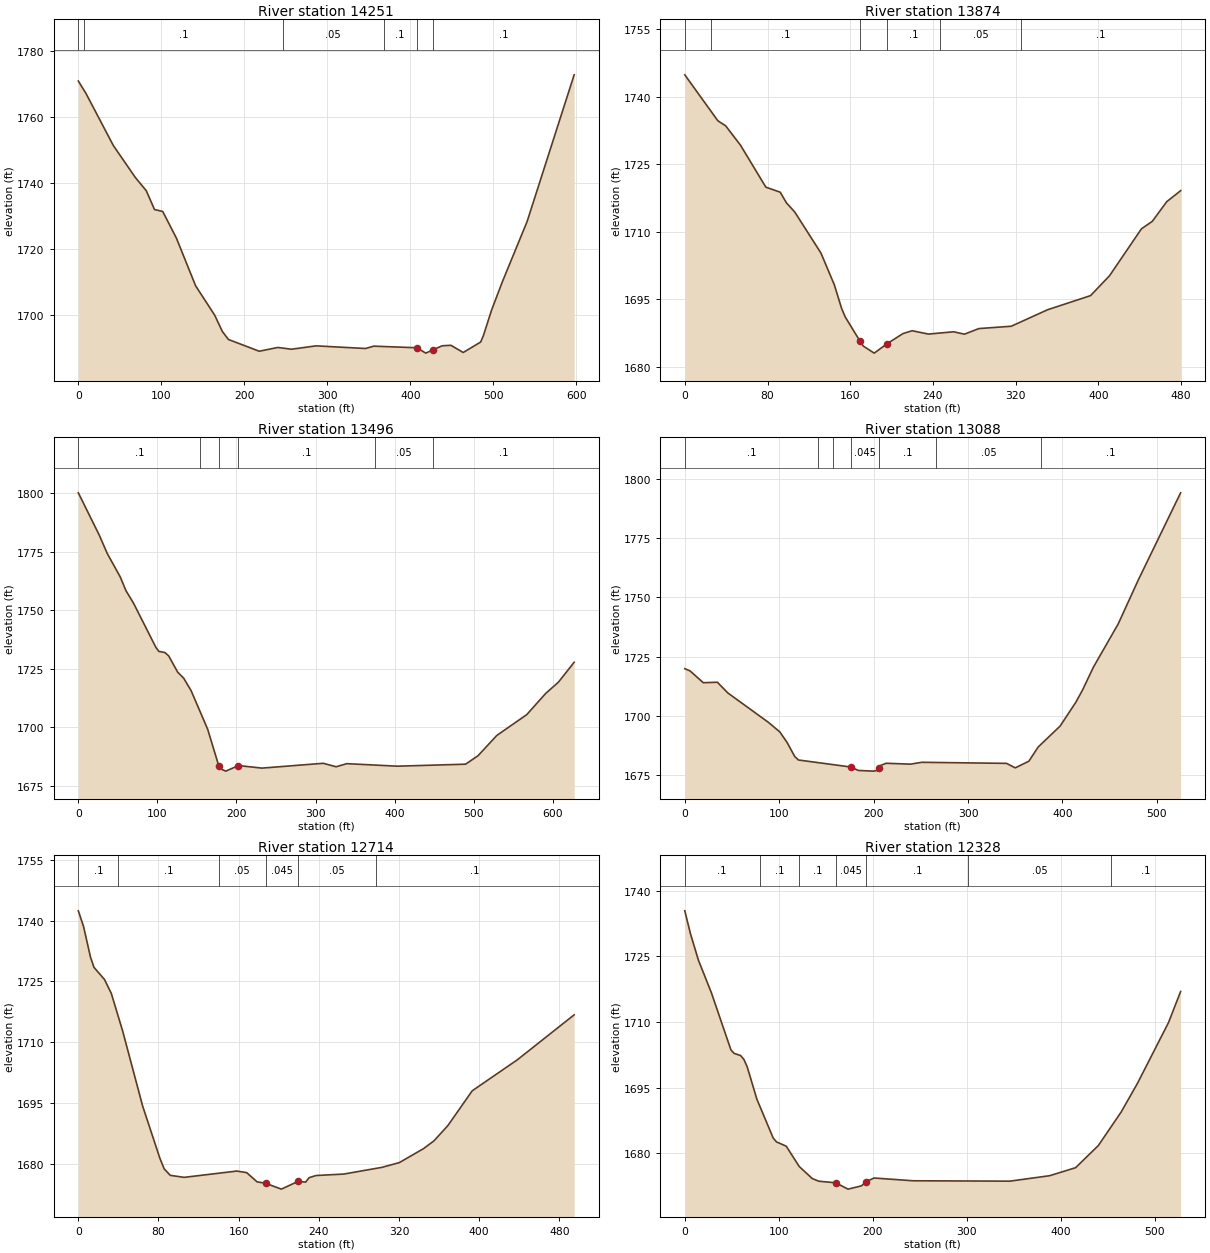
Type RM Length L Ch R = 1 ,14251   ,380.4,377.9,370.6
XS GIS Cut Line= 2
2077560.37179911310426.5641901342076966.83886543310494.923633456
#Sta/Elev= 30
       0 1770.93     9.2 1767.17    42.2  1751.4    68.7 1741.74    81.9 1737.73
    91.8 1732.04   101.7 1731.45   118.2 1723.39   141.3 1708.98   164.4 1700.04
   173.5 1695.17   180.9 1692.72     218 1689.16   240.4  1690.3   256.9 1689.77
   286.6 1690.79   346.1 1689.99     356  1690.7  407.861690.214   418.7 1688.59
  427.881689.647   438.5 1690.81     449 1690.96   463.8 1688.78   484.8 1691.94
   488.1 1693.86     498 1701.62   511.1 1710.25   540.8  1728.4   597.5  1772.8
#Mann= 6 ,-1 , 0
       0      .1       0    7.03      .1       0  246.32     .05       0
  367.77      .1       0  407.86    .045       0  427.88      .1       0
Bank Sta=407.86,427.88
XS Rating Curve= 0 ,0
Exp/Cntr=0.3,0.1

Type RM Length L Ch R = 1 ,13874   ,377.9,377.2,370.6
XS GIS Cut Line= 2
2077434.50361252 310114.064487042076984.19972309310278.994931459
#Sta/Elev= 30
       0 1744.82    31.9 1734.64    39.6 1733.48    53.9 1729.19    78.4 1719.88
    92.3 1718.76    98.4 1716.37   106.3 1714.38   131.7 1705.25   144.7 1698.16
   151.7 1692.94   155.2 1691.05  169.641685.638   172.7 1684.59   183.2 1683.03
  195.741685.124   211.1 1687.38     220    1688   235.6 1687.26     260 1687.77
   270.5 1687.24   284.5 1688.48   315.8    1689   350.9 1692.66   392.5  1695.8
   410.8  1700.2   441.7 1710.63   452.2 1712.29   466.2 1716.66   479.6  1719.1
#Mann= 6 ,-1 , 0
       0      .1       0      25      .1       0  169.64    .045       0
  195.74      .1       0  246.94     .05       0  325.03      .1       0
Bank Sta=169.64,195.74
XS Rating Curve= 0 ,0
Exp/Cntr=0.3,0.1

Type RM Length L Ch R = 1 ,13496   ,404.3,408,406.9
XS GIS Cut Line= 2
2077347.69801185309704.9931267052076843.14095011310077.171844289
#Sta/Elev= 30
       0 1800.15    26.2 1782.26    36.6 1774.22    52.9 1764.27    60.3 1758.28
    69.7 1753.05    98.1 1734.07   101.8 1732.38   109.6 1731.87   114.3 1730.43
   125.7 1723.46   133.1 1720.99   142.6 1715.61   163.6 1699.06  177.581683.487
     180 1682.15   186.5  1681.2  202.461683.583   232.2 1682.49   309.7 1684.55
     326 1683.06   339.5 1684.39   403.5 1683.31   489.7 1684.17   505.4 1687.77
   529.2 1696.45   567.1 1705.36     591 1714.42     607 1719.18     627 1727.74
#Mann= 6 ,-1 , 0
       0      .1       0  154.29      .1       0  177.58    .045       0
  202.46      .1       0  374.92     .05       0  448.69      .1       0
Bank Sta=177.58,202.46
XS Rating Curve= 0 ,0
Exp/Cntr=0.3,0.1

Type RM Length L Ch R = 1 ,13088   ,367.1,374.2,373.9
XS GIS Cut Line= 2
2077030.85776627309484.7242102922076595.74511945 309778.77775605
#Sta/Elev= 30
       0 1719.97     5.5 1719.07    19.6 1714.07    34.5 1714.27    45.5 1709.79
    88.7 1697.33   100.6 1693.36   108.5 1688.81   116.4 1682.99   120.4  1681.5
  176.141678.532   183.7  1677.1   199.6 1676.81   203.5 1677.05   205.51678.034
   207.5  1679.2   213.3 1680.12   239.1 1679.75     251 1680.53   340.9 1680.08
     350 1678.18   364.5    1681   374.3 1686.97   397.6 1695.82   414.2 1705.84
   421.3 1710.99   432.9 1720.68   459.1 1738.85   480.3 1757.31   525.2 1794.09
#Mann= 7 ,-1 , 0
       0      .1       0  141.18     .05       0  156.67      .1       0
  176.14    .045       0   205.5      .1       0  266.12     .05       0
  376.99      .1       0
Bank Sta=176.14,205.5
XS Rating Curve= 0 ,0
Exp/Cntr=0.3,0.1

Type RM Length L Ch R = 1 ,12714   ,385.3,386.6,385.1
XS GIS Cut Line= 2
2076985.28502277309226.4776795512076516.53497604309384.897638291
#Sta/Elev= 30
       0 1742.41     5.2 1738.57    12.1 1731.03    15.6 1728.49    26.1  1725.5
    32.9 1722.07    44.3 1712.75    64.1 1694.38    81.4 1681.44    85.7 1678.83
    91.8 1677.24   105.6 1676.75   158.1  1678.3     168 1677.92   178.4 1675.64
  186.781675.306   202.6 1673.85  219.551675.785   226.8 1675.57   230.3 1676.67
   237.2  1677.2   264.9 1677.56   303.1 1679.22   320.4 1680.39   344.3  1683.8
   354.9 1685.74   368.8 1689.51   393.1 1698.08   438.1 1705.71   494.8 1716.79
#Mann= 6 ,-1 , 0
       0      .1       0   39.77      .1       0  140.47     .05       0
  186.78    .045       0  219.55     .05       0  297.31      .1       0
Bank Sta=186.78,219.55
XS Rating Curve= 0 ,0
Exp/Cntr=0.3,0.1

Type RM Length L Ch R = 1 ,12328   ,394.1,401.3,402.3
XS GIS Cut Line= 2
2076839.88570726308896.6164626332076339.66853186  309063.7171783
#Sta/Elev= 30
       0 1735.43       6 1730.22    14.5 1724.14    28.3 1716.69    49.1 1703.61
    52.5 1702.83    59.4 1702.33    62.9 1701.44    66.4 1699.74    76.7 1692.34
      94 1683.49    97.5 1682.59   107.9 1681.61   121.7 1676.97   135.5 1674.22
   142.5  1673.6  160.511673.242   173.6 1671.79   187.8 1672.53  193.271673.519
   201.3 1674.33   242.8  1673.7   345.7 1673.61   388.1 1674.86   415.7 1676.69
   439.9 1681.76   464.2 1689.44   481.5 1695.98   514.5 1709.87   527.4 1716.98
#Mann= 7 ,-1 , 0
       0      .1       0   79.47      .1       0  121.56      .1       0
  160.51    .045       0  193.27      .1       0  301.47     .05       0
  453.22      .1       0
Bank Sta=160.51,193.27
XS Rating Curve= 0 ,0
Exp/Cntr=0.3,0.1

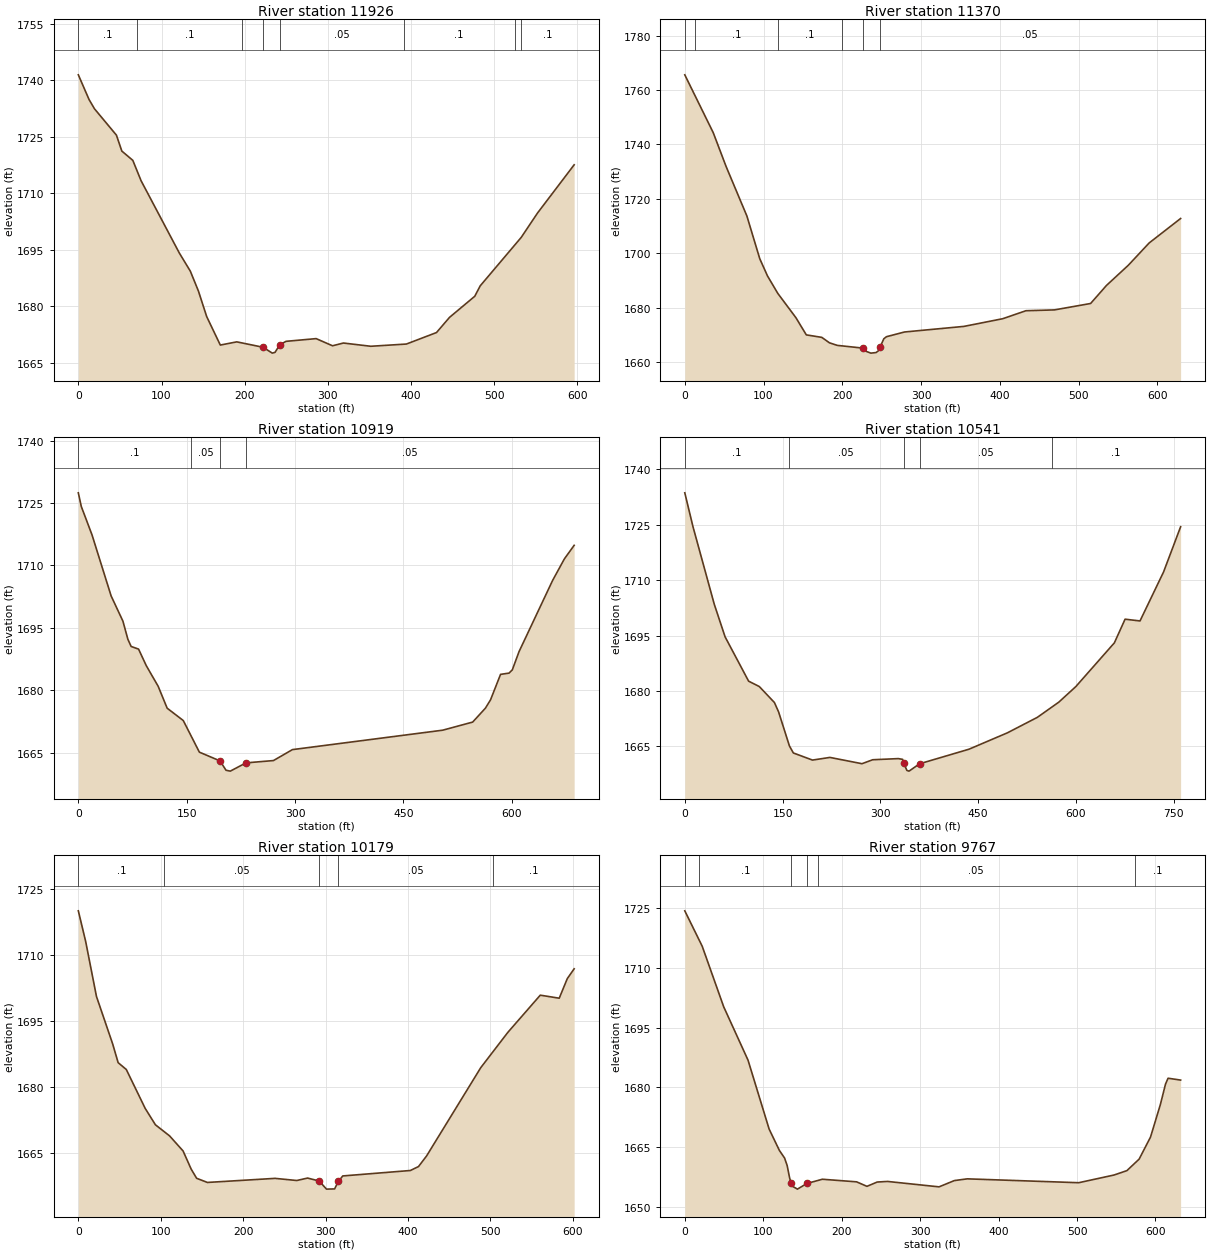
Type RM Length L Ch R = 1 ,11926   ,549.8,556,548.1
XS GIS Cut Line= 2
2076816.01403585308617.7535032932076221.39613062308575.436002627
#Sta/Elev= 30
       0 1741.44    12.9 1734.88    19.4 1732.43    45.8 1725.43    52.3  1721.2
    65.5 1718.74    75.4 1713.35   121.4 1694.15   134.6 1689.35   144.4 1684.04
   154.3 1677.28   170.7 1669.71   190.5 1670.56   222.11669.128   233.2 1667.57
   236.5 1667.78  242.161669.778   249.7  1670.7   285.9 1671.42   305.6 1669.52
   318.7 1670.25   351.6 1669.39   394.4 1669.98   430.6 1673.03   446.3 1677.07
   476.6 1682.66   483.2 1685.44   532.5  1698.3     552 1704.74   596.1 1717.56
#Mann= 8 ,-1 , 0
       0      .1       0   70.87      .1       0  196.33     .05       0
   222.1    .045       0  242.16     .05       0   391.5      .1       0
  524.39     .05       0  532.48      .1       0
Bank Sta=222.1,242.16
XS Rating Curve= 0 ,0
Exp/Cntr=0.3,0.1

Type RM Length L Ch R = 1 ,11370   ,461.4,451.1,434.9
XS GIS Cut Line= 2
2076780.20669279308124.0471416262076150.86641604308142.493298963
#Sta/Elev= 30
       0  1765.6    36.1 1744.34    52.5 1731.86    78.8 1713.73    95.2 1697.99
     105 1691.67   118.1 1685.24   141.1 1676.31   154.3 1669.99   173.9 1669.08
   183.7 1667.07   193.6 1666.13  226.341665.118   229.7 1663.99   236.3 1663.28
   242.9 1663.49   246.2 1664.22  247.861665.429   252.7 1668.54     256 1669.31
     279 1671.05   354.5 1673.11   403.7 1675.93   433.2 1678.87   469.3 1679.17
   515.3 1681.53   535.5 1688.18   563.2 1695.59   589.6 1703.77   629.6 1712.78
#Mann= 6 ,-1 , 0
       0      .1       0   13.49      .1       0  118.88      .1       0
  199.65     .05       0  226.34    .045       0  247.86     .05       0
Bank Sta=226.34,247.86
XS Rating Curve= 0 ,0
Exp/Cntr=0.3,0.1

Type RM Length L Ch R = 1 ,10919   ,362.7,378.3,383.5
XS GIS Cut Line= 2
2076569.70317677307602.1285660422076115.05907294308116.451356292
#Sta/Elev= 30
       0 1727.45     4.1 1724.17      19 1717.32    45.4 1702.67    61.7 1696.62
    68.6 1692.25    73.1 1690.52    83.4 1689.88    94.2 1685.86   110.5 1680.96
     123 1675.68   145.3 1672.71   167.6 1665.11  196.13 1663.01   204.5 1660.76
   210.4 1660.55  232.091662.532   270.2 1663.09   296.4 1665.72   504.5 1670.39
     546 1672.34   563.6 1675.68   570.7 1677.68   584.6 1683.81   596.3 1684.11
   600.9  1684.9   610.2 1689.28   656.7  1706.4     673 1711.58   686.5 1714.83
#Mann= 4 ,-1 , 0
       0      .1       0  155.92     .05       0  196.13    .045       0
  232.09     .05       0
Bank Sta=196.13,232.09
XS Rating Curve= 0 ,0
Exp/Cntr=0.3,0.1

Type RM Length L Ch R = 1 ,10541   ,358.5,361.6,358.8
XS GIS Cut Line= 2
2076563.19301918307535.9393939672075802.55936986307532.684151128
#Sta/Elev= 30
       0 1733.68    12.6 1724.48    45.2 1703.52    61.8 1694.69    97.9 1682.69
   114.3 1681.23   137.5  1676.9   143.9 1674.36   160.5 1665.15   166.5 1663.25
   195.9 1661.32   222.6 1662.04   271.8 1660.34   288.2 1661.41   327.6 1661.72
   334.2 1661.51  335.671660.575   340.7 1658.51     344 1658.33  360.141660.316
   435.9 1664.26   494.9  1668.7   540.8 1672.89   573.7    1677   599.9 1681.23
     659 1693.07   675.4 1699.47   698.3 1698.99   734.4 1712.24   760.6 1724.49
#Mann= 5 ,-1 , 0
       0      .1       0  159.35     .05       0  335.67    .045       0
  360.14     .05       0  562.96      .1       0
Bank Sta=335.67,360.14
XS Rating Curve= 0 ,0
Exp/Cntr=0.3,0.1

Type RM Length L Ch R = 1 ,10179   ,408.9,411.9,409.6
XS GIS Cut Line= 2
2076480.72763294307275.5225919632075879.59924203307254.906491458
#Sta/Elev= 30
       0 1720.08     8.9 1713.11      22 1700.59    41.7 1689.76    48.3 1685.52
    58.2 1683.96    81.1 1675.11    93.5 1671.38   110.7 1668.85   127.1 1665.41
   136.9 1661.28   143.5  1659.2   156.6 1658.25   238.7 1659.18     265 1658.69
   278.1 1659.25  292.111658.582   301.1 1656.73   310.9 1656.78  315.361658.468
   320.8 1659.73   402.8 1660.97   412.7 1661.87   422.5 1664.29   488.2 1684.38
     521  1692.4   560.4 1700.88   583.4 1700.19   593.2 1704.66   601.5 1706.88
#Mann= 5 ,-1 , 0
       0      .1       0  104.34     .05       0  292.11    .045       0
  315.36     .05       0  502.62      .1       0
Bank Sta=292.11,315.36
XS Rating Curve= 0 ,0
Exp/Cntr=0.3,0.1

Type RM Length L Ch R = 1 ,9767    ,709.9,718.4,695.7
XS GIS Cut Line= 3
2076500.54813135306989.7154207972076302.63153243306986.243314877
2075868.60385719306977.562557966
#Sta/Elev= 30
       0 1724.31    22.2 1715.42    49.6 1700.22    80.6 1686.83   107.5 1669.53
   120.6 1664.16   127.2 1662.26   130.5 1660.37   133.7 1657.19  135.681655.989
     137  1655.2   143.6 1654.45  155.691655.875   175.4 1656.93     219 1656.28
   232.2 1655.15   245.3 1656.23   258.4 1656.38   324.1 1655.02   343.7  1656.6
   360.2 1657.03   502.2 1656.06   547.2 1657.99   563.6 1659.09   579.2 1661.98
   593.7 1667.51   606.3 1675.69   612.8  1680.8   616.1 1682.29   632.1 1681.82
#Mann= 6 ,-1 , 0
       0      .1       0   18.64      .1       0  135.68    .045       0
  155.69      .1       0  169.71     .05       0   573.3      .1       0
Bank Sta=135.68,155.69
XS Rating Curve= 0 ,0
Exp/Cntr=0.3,0.1

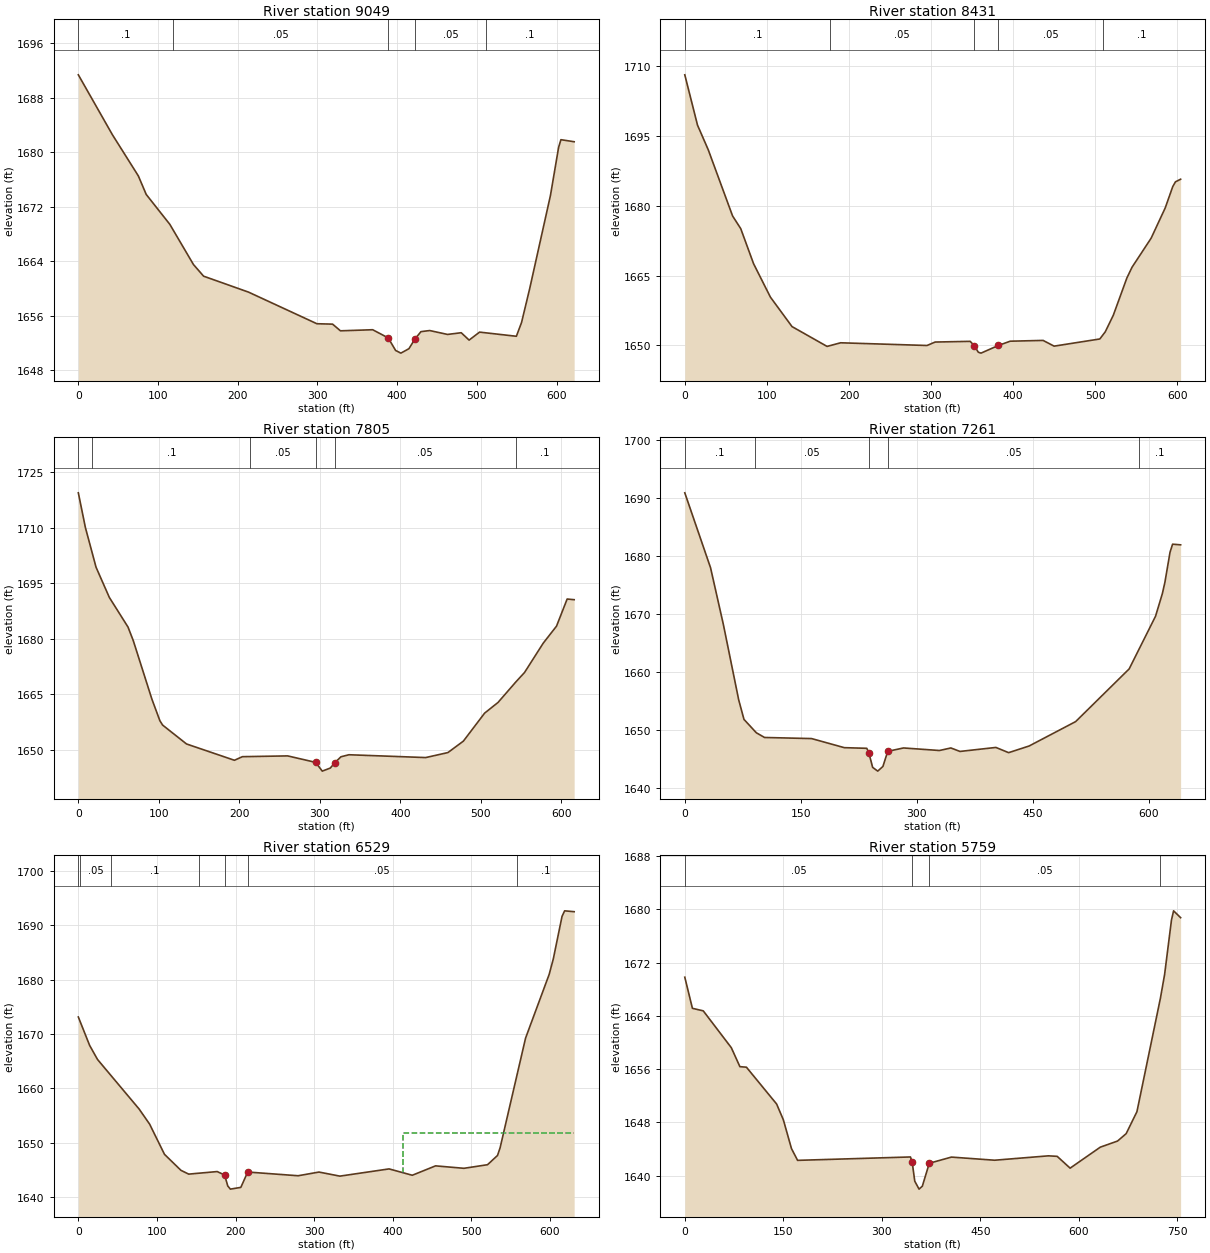
Type RM Length L Ch R = 1 ,9049    ,613.6,618.3,611.8
XS GIS Cut Line= 2
 2076477.9786227306564.3681743742075858.18721136 306618.18762055
#Sta/Elev= 30
       0 1691.33    42.8 1682.54    75.3 1676.51    85.2 1673.79   114.8 1669.41
   144.5 1663.51   157.2 1661.81   213.6 1659.47   299.3 1654.84     319 1654.78
   328.9  1653.8   369.3 1653.96  388.821652.761   398.1 1650.92   404.7 1650.53
   414.8 1651.18  422.391652.606   429.9 1653.68   440.9 1653.84   463.2 1653.27
   480.4 1653.52   490.3 1652.44   503.4 1653.61   549.6    1653   556.1 1655.02
   566.3 1659.98   592.4 1673.67   602.6  1680.7   605.5 1681.82   622.1 1681.52
#Mann= 5 ,-1 , 0
       0      .1       0  119.24     .05       0  388.82    .045       0
  422.39     .05       0  511.12      .1       0
Bank Sta=388.82,422.39
XS Rating Curve= 0 ,0
Exp/Cntr=0.3,0.1

Type RM Length L Ch R = 1 ,8431    ,613.8,626.2,620.7
XS GIS Cut Line= 2
2076408.53420776306086.9376987962075806.10365412306128.604282126
#Sta/Elev= 30
       0 1708.11    15.5  1697.3    28.6    1692    58.2  1677.8    68.1 1675.09
    83.8 1667.53   104.3 1660.36   130.6 1654.04   173.3 1649.78   189.8 1650.56
     295 1649.98   304.9 1650.72   347.6 1650.87  352.531649.964   357.5 1648.53
   360.8 1648.34  381.911649.982   396.3  1650.9   436.4 1651.07   449.8 1649.84
   505.5 1651.38   512.1 1652.91   521.9 1656.47   538.4 1664.46   544.7 1666.78
     568 1673.03   585.2 1679.55   594.3  1684.1   597.6 1685.13   603.9 1685.69
#Mann= 5 ,-1 , 0
       0      .1       0  177.23     .05       0  352.53    .045       0
  381.91     .05       0  509.62      .1       0
Bank Sta=352.53,381.91
XS Rating Curve= 0 ,0
Exp/Cntr=0.3,0.1

Type RM Length L Ch R = 1 ,7805    ,528.9,544.1,535
XS GIS Cut Line= 2
2076405.06210187305741.4515131262075793.95111936305665.062558293
#Sta/Elev= 30
       0  1719.4     8.8 1710.01      22 1699.32    38.5 1691.17    61.7 1683.17
    68.3 1679.47    91.4 1663.69   101.3 1657.88   104.7  1656.7   134.4  1651.6
   193.9  1647.2   203.8 1648.17     260 1648.38  294.831646.632     303 1644.27
     313  1645.1  318.731646.563   326.2 1648.14   336.1 1648.69   431.5 1647.93
   459.1 1649.28   478.3 1652.37   504.7 1659.93   521.3  1662.8   543.2 1668.28
   554.3 1670.91   577.5 1678.82     594 1683.41   607.2 1690.73   615.9 1690.55
#Mann= 6 ,-1 , 0
       0      .1       0   17.39      .1       0  213.65     .05       0
  294.83    .045       0  318.73     .05       0   543.2      .1       0
Bank Sta=294.83,318.73
XS Rating Curve= 0 ,0
Exp/Cntr=0.3,0.1

Type RM Length L Ch R = 1 ,7261    ,729.5,731.5,720.9
XS GIS Cut Line= 3
2076425.89539352305489.7154680492076101.24249953305435.896021873
2075792.21490237305394.229110464
#Sta/Elev= 30
       0 1690.96    33.3 1678.02    49.9  1668.2    69.7  1655.2    76.5 1651.84
    92.5 1649.53   103.1 1648.72   163.9 1648.53   206.2 1646.96   235.2 1646.85
  237.851646.103   242.8 1643.56   249.4 1642.91   256.1 1643.72  262.331646.326
   282.7 1646.91   329.2 1646.47   343.9 1646.91   355.7 1646.31   402.1    1647
   418.6  1646.1   445.1 1647.25   505.2 1651.46   574.4 1660.56   608.5 1669.66
   617.3 1673.56   620.6 1675.52   627.2  1680.7   630.5 1682.09   640.9 1681.98
#Mann= 5 ,-1 , 0
       0      .1       0   90.32     .05       0  237.85    .045       0
  262.33     .05       0  587.32      .1       0
Bank Sta=237.85,262.33
XS Rating Curve= 0 ,0
Exp/Cntr=0.3,0.1

Type RM Length L Ch R = 1 ,6529    ,746.4,769.7,748.5
XS GIS Cut Line= 3
2076417.21496469304882.076591462 2076068.2566731304932.423603624
2075790.47868535304946.312683463
#Sta/Elev= 30
       0 1673.11    14.4 1667.88    24.4  1665.3    77.4 1656.17    90.7  1653.4
   109.6 1647.85   130.5 1644.91   140.4 1644.21   176.6 1644.68  186.08 1644.05
   190.1 1642.03   193.4 1641.45   206.7 1641.77  215.461644.595   279.6 1643.91
   306.1 1644.59   332.7 1643.84   395.3 1645.17   424.8    1644   454.4 1645.73
   490.5 1645.28   520.5 1645.94   533.2 1647.64   536.5 1649.05   568.9 1669.23
   598.9 1680.94   604.2 1683.81   615.3 1691.63   618.6 1692.64   630.7 1692.48
#Mann= 7 ,-1 , 0
       0      .1       0    2.21     .05       0   41.22      .1       0
  152.88     .05       0  186.08    .045       0  215.46     .05       0
  557.38      .1       0
#XS Ineff= 2 , 0
                          413.19         1651.83
Permanent Ineff=
       F       F
Bank Sta=186.08,215.46
XS Rating Curve= 0 ,0
Exp/Cntr=0.3,0.1

Type RM Length L Ch R = 1 ,5759    ,846,864.6,844.3
XS GIS Cut Line= 3
2076480.14889395304401.173681885 2076014.0031727304375.132067293
2075726.24259335304364.715421468
#Sta/Elev= 30
       0 1669.81    11.6 1665.14    28.1 1664.76    70.8 1659.23    83.9 1656.38
    93.8  1656.3   139.8 1650.77     150 1648.41   162.4 1644.08   171.7 1642.31
   343.5 1642.82  346.071642.103   350.1 1639.18   356.6 1637.99   361.6 1638.43
  372.191641.873   405.9  1642.8   471.7 1642.33   553.7 1642.99   566.9 1642.91
   586.6 1641.14   632.5 1644.29   658.8 1645.21   671.9 1646.32   688.3 1649.62
     724 1666.64   730.4 1670.21   740.9 1678.42   744.1 1679.78   754.8 1678.75
#Mann= 4 ,-1 , 0
       0     .05       0  346.07    .045       0  372.19     .05       0
     724      .1       0
Bank Sta=346.07,372.19
XS Rating Curve= 0 ,0
Exp/Cntr=0.5,0.3

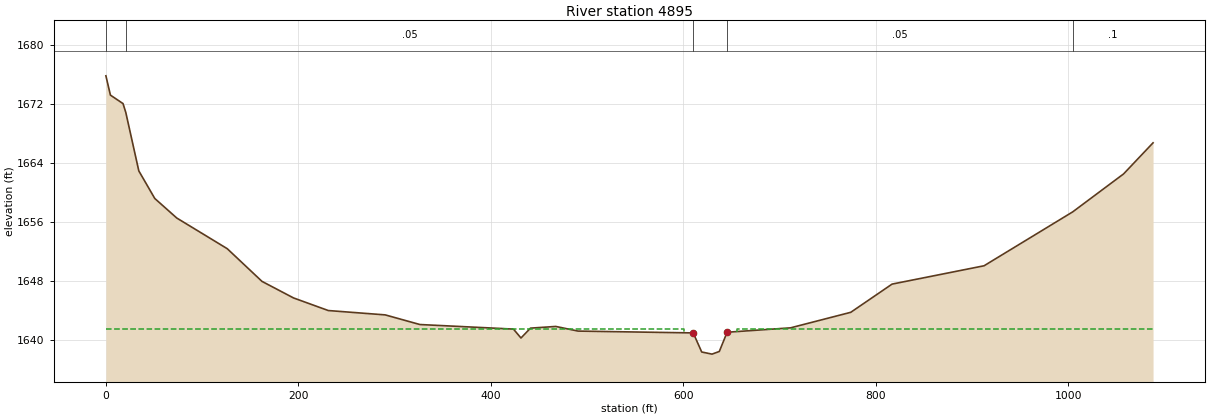
Type RM Length L Ch R = 1 ,4895    ,44.6,46.4,47.3
XS GIS Cut Line= 3
2076640.54260203303955.328444958 2076213.4591386303964.008873791
2075555.47324985  304026.5087488
#Sta/Elev= 30
       0 1675.83     4.7 1673.21    17.8 1672.06    20.7 1670.84    34.2 1662.92
    50.8 1659.17    73.6 1656.52   126.1 1652.35   162.2 1647.91     195 1645.66
   231.1 1643.95   290.2 1643.36   326.3 1642.05   423.5 1641.43   431.3 1640.22
   441.2 1641.56   467.5 1641.79   490.6 1641.16   610.3 1640.91   619.1 1638.32
   629.8 1638.03   637.4 1638.39   645.5    1641   711.4  1641.6     774 1643.71
   816.9 1647.54   912.5 1650.03  1004.6 1657.35  1057.5 1662.51  1088.1 1666.73
#Mann= 5 ,-1 , 0
       0      .1       0    20.7     .05       0   610.3    .045       0
   645.5     .05       0  1004.6      .1       0
#XS Ineff= 2 , 0
           600.3  1641.4   655.5          1641.4
Permanent Ineff=
       F       F
Bank Sta=610.3,645.5
XS Rating Curve= 0 ,0
Exp/Cntr=0.5,0.3