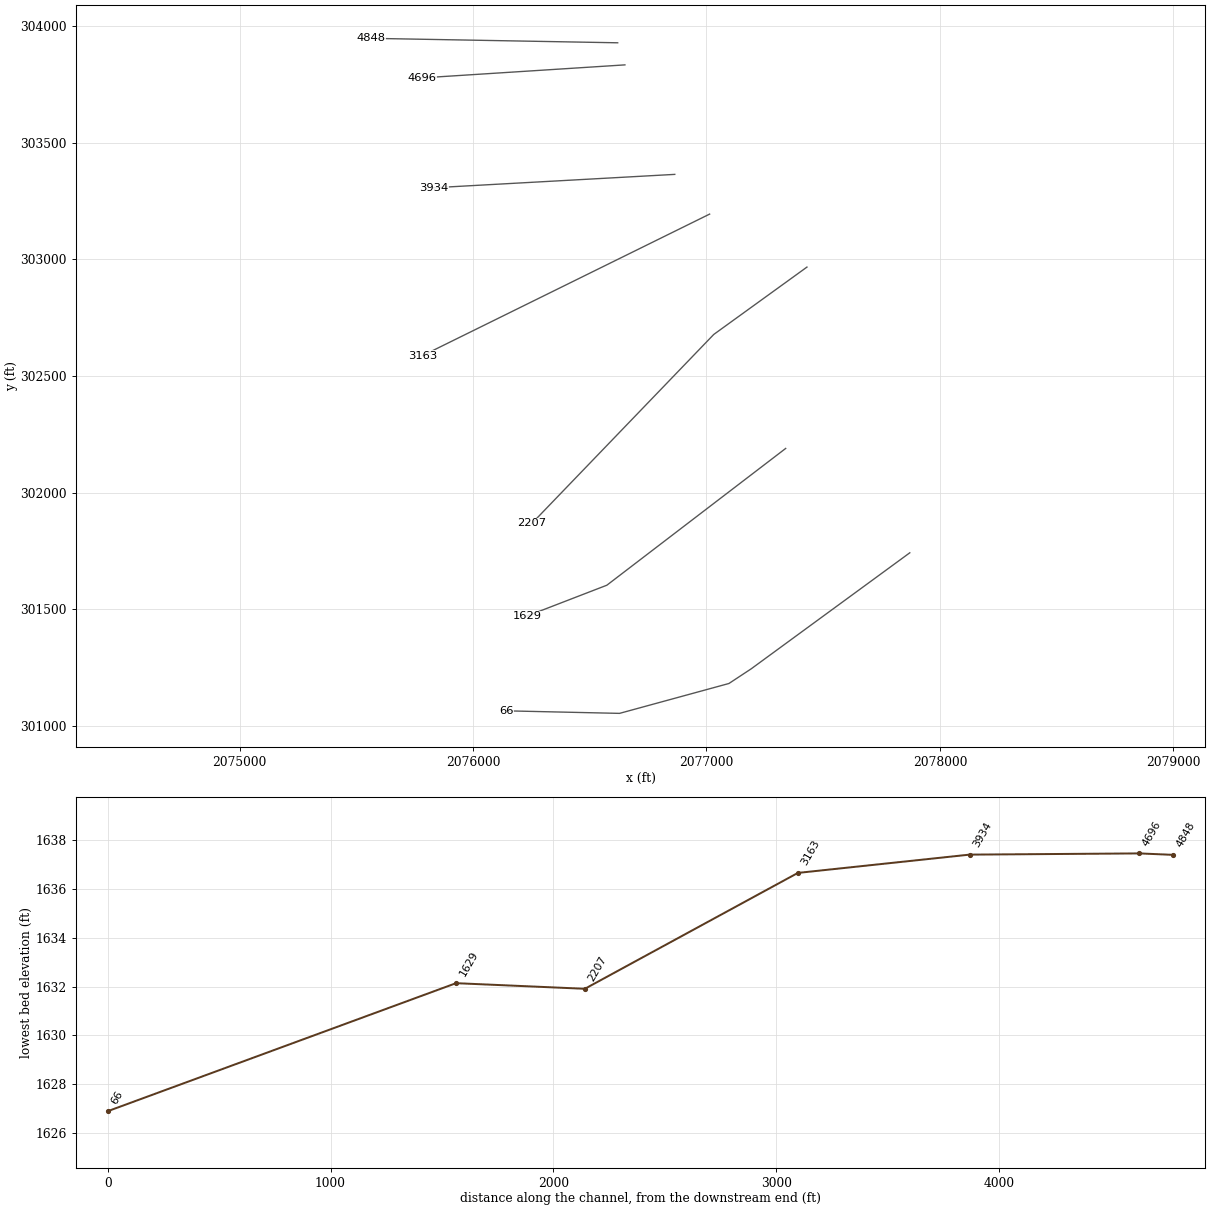
HEC-RAS study RENICKCK.prj: RENICKCK

--- RENICKCK.g01 (geometry) --- (continued)

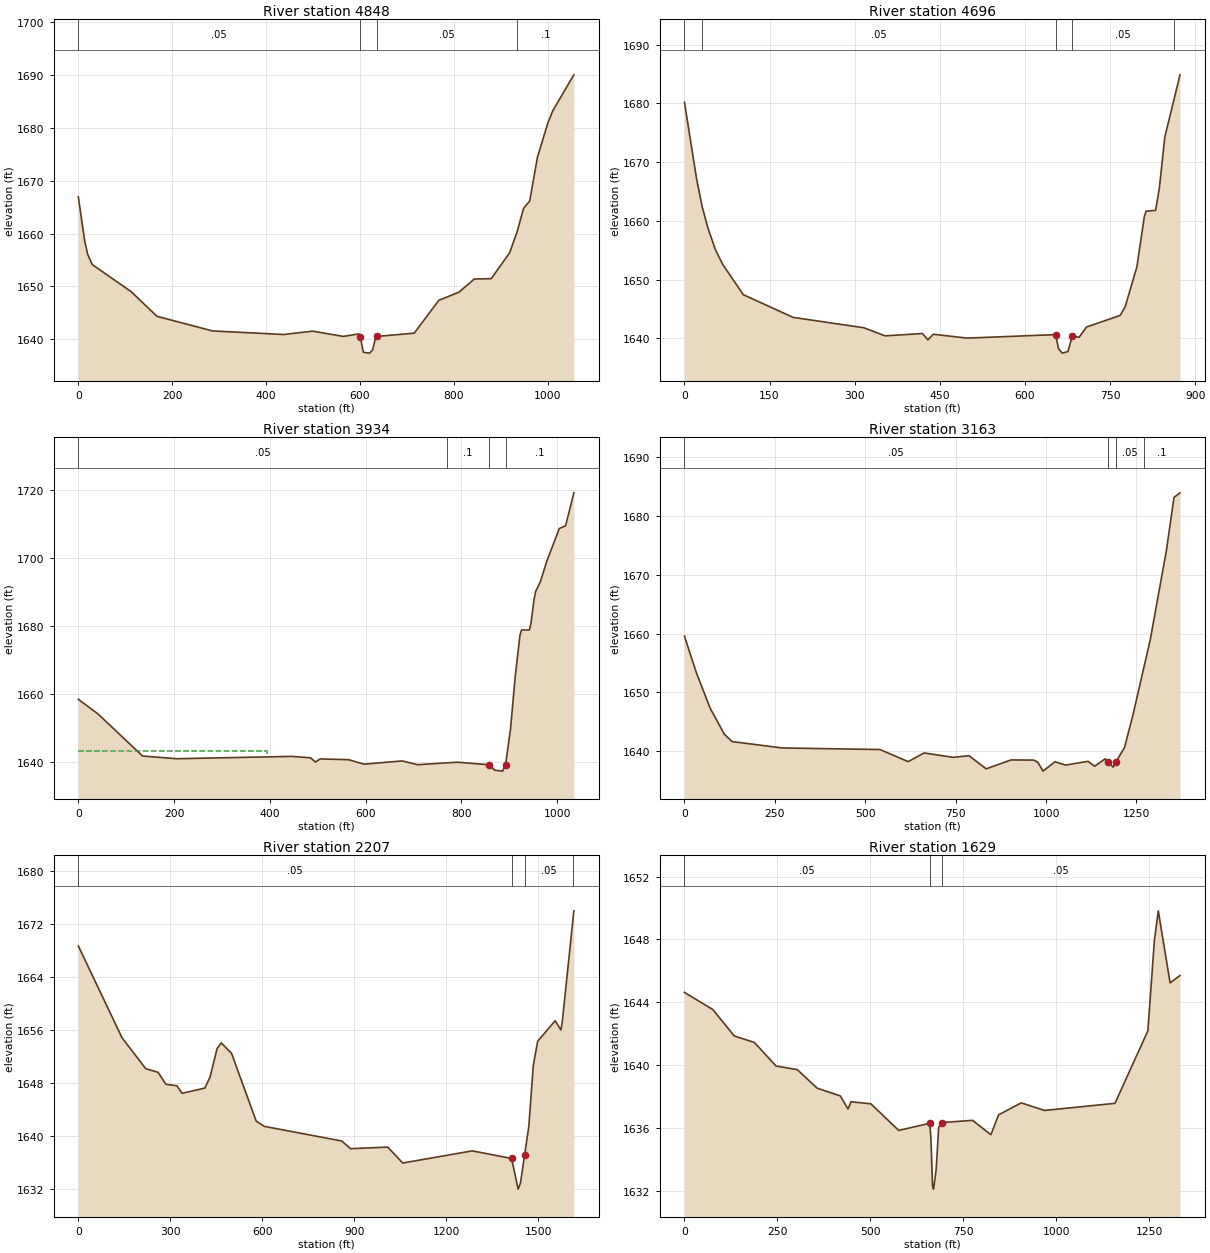
Type RM Length L Ch R = 1 ,4848    ,151.2,152.7,153
XS GIS Cut Line= 2
2076619.70931035303927.5506133742075564.15367869303946.647688046
#Sta/Elev= 30
       0 1666.95    13.4 1658.71    19.9 1656.09    29.8 1654.14   111.8 1649.08
   167.6 1644.36   285.7  1641.6   437.7 1640.92   499.1 1641.56   564.6 1640.56
   597.5 1641.03   600.7 1640.43   607.3 1637.56   620.4  1637.4     627    1638
   633.6 1640.41   636.2 1640.55   715.6 1641.18   768.1 1647.39   810.7 1648.91
   843.6 1651.41   879.7 1651.48     919 1656.38   935.4 1660.51   948.6 1664.77
   961.7 1666.18   978.1 1674.43  1000.4 1680.92  1010.9 1683.24  1055.7 1690.02
#Mann= 4 ,-1 , 0
       0     .05       0   600.7    .045       0   636.2     .05       0
   935.4      .1       0
Bank Sta=600.7,636.2
XS Rating Curve= 0 ,0
Exp/Cntr=0.5,0.3

Type RM Length L Ch R = 1 ,4696    ,747,762,751.7
XS GIS Cut Line= 2
2076650.72171551303832.9445033822075779.19393101 303777.04172805
#Sta/Elev= 30
       0 1680.19    21.3 1667.19    31.3 1662.39    41.2 1658.82    54.3 1655.15
    67.5 1652.56   103.7 1647.42   191.5 1643.55   316.4 1641.78   353.5  1640.4
   419.3  1640.8   429.1 1639.72   438.6 1640.68   498.2 1640.02  654.171640.612
   659.3 1638.22   665.8 1637.46   675.7 1637.72  683.611640.376   695.4 1640.15
   708.6 1641.91   767.7 1643.88   776.6 1645.33   797.3 1652.15   810.5 1660.76
   813.8 1661.65   830.2 1661.78   836.8 1665.47   846.6  1674.3   873.3 1684.88
#Mann= 5 ,-1 , 0
       0      .1       0   31.32     .05       0  654.17    .045       0
  683.61     .05       0  862.73      .1       0
Bank Sta=654.17,683.61
XS Rating Curve= 0 ,0
Exp/Cntr=0.3,0.1

Type RM Length L Ch R = 1 ,3934    ,762.6,770.5,771
XS GIS Cut Line= 2
2076864.26361129303363.8473444582075831.27748826303306.555792376
#Sta/Elev= 30
       0 1658.56    41.5 1654.18   134.1 1641.86   205.8 1641.06   445.6 1641.75
     485 1641.33   494.9 1640.08   504.8    1641   563.9 1640.78   596.8 1639.46
   675.8 1640.41   708.5  1639.3     791 1640.04  857.781639.284   869.5 1637.68
   885.9 1637.41   892.1 1639.35   902.4 1649.85   912.2 1665.25   922.1 1677.41
   925.4 1678.94   941.8 1678.95   945.1 1680.91   951.6 1688.01   954.9  1690.3
   964.8 1693.14   977.9 1699.11  1004.2 1708.78  1017.4 1709.62  1034.6 1719.29
#Mann= 4 ,-1 , 0
       0     .05       0  769.29      .1       0  857.78    .045       0
   892.1      .1       0
#XS Ineff= 2 , 0
          392.97 1643.33
Permanent Ineff=
       F       F
Bank Sta=857.78,892.1
XS Rating Curve= 0 ,0
Exp/Cntr=0.3,0.1

Type RM Length L Ch R = 1 ,3163    ,934.1,955.7,945.5
XS GIS Cut Line= 2
2077013.56908694303193.7085771262075784.40225393302587.805589467
#Sta/Elev= 30
       0 1659.54    33.4 1653.27    71.3 1647.31   110.2 1642.93   131.7 1641.67
   270.6 1640.59   540.8 1640.32   618.6 1638.27   662.5 1639.74     743    1639
   786.9 1639.27   834.4 1637.05   903.4 1638.56   966.1 1638.53   977.1 1638.18
   991.6 1636.66  1024.6 1638.25  1053.9 1637.69  1116.1 1638.32  1134.4 1637.49
  1163.6 1638.75 1171.251638.215  1185.6 1637.34 1193.351638.233    1217 1640.68
  1240.4 1646.21  1288.1 1658.93  1332.8 1674.06  1353.8 1683.08  1370.4 1683.86
#Mann= 4 ,-1 , 0
       0     .05       0 1171.25    .045       0 1193.35     .05       0
 1271.34      .1       0
Bank Sta=1171.25,1193.35
XS Rating Curve= 0 ,0
Exp/Cntr=0.3,0.1

Type RM Length L Ch R = 1 ,2207    ,565.3,578.1,561.6
XS GIS Cut Line= 3
2077430.52494594302966.7119838742077031.21964219302678.083296046
2076252.13950744301868.621660382
#Sta/Elev= 30
       0 1668.71   142.5 1654.82     220 1650.13     260 1649.59   285.8 1647.77
   321.6 1647.55   338.4 1646.41   412.7  1647.2     430 1648.91   452.6 1653.19
   466.4 1654.02   499.6 1652.47   580.2  1642.2   606.3 1641.41   859.4 1639.19
   887.8 1638.03  1009.3 1638.27  1058.1 1635.86  1285.2  1637.7  1413.1 1636.55
  1434.6 1631.91  1441.9 1632.79 1455.681637.101  1469.4 1641.43  1483.9 1650.59
  1498.1 1654.28  1555.3 1657.39  1573.9 1655.99  1578.5 1657.24  1616.2 1674.02
#Mann= 4 ,-1 , 0
       0     .05       0  1413.1    .045       0 1455.68     .05       0
 1613.69      .1       0
Bank Sta=1413.1,1455.68
XS Rating Curve= 0 ,0
Exp/Cntr=0.3,0.1

Type RM Length L Ch R = 1 ,1629    ,1508.7,1563.2,1532.1
XS GIS Cut Line= 3
2077339.37913087302189.8021203732076573.32029551301603.864643961
2076230.43810728301471.486299798
#Sta/Elev= 30
       0 1644.64    76.1 1643.55     134 1641.87   187.7 1641.46   246.4 1639.96
   303.3 1639.73     357 1638.55   419.1 1638.06   439.6 1637.23   447.9 1637.69
     501 1637.56   575.9 1635.87  659.371636.322   662.5 1635.35   666.8 1632.33
   669.5 1632.14   676.5 1633.36   683.3 1636.06  692.181636.368   774.2 1636.51
   823.8  1635.6   844.4 1636.86   905.2 1637.62   967.7 1637.14  1157.2 1637.59
  1245.6 1642.19  1263.2 1647.95  1273.7 1649.82  1305.4 1645.24    1332 1645.71
#Mann= 3 ,-1 , 0
       0     .05       0  659.37    .045       0  692.18     .05       0
Bank Sta=659.37,692.18
XS Rating Curve= 0 ,0
Exp/Cntr=0.3,0.1

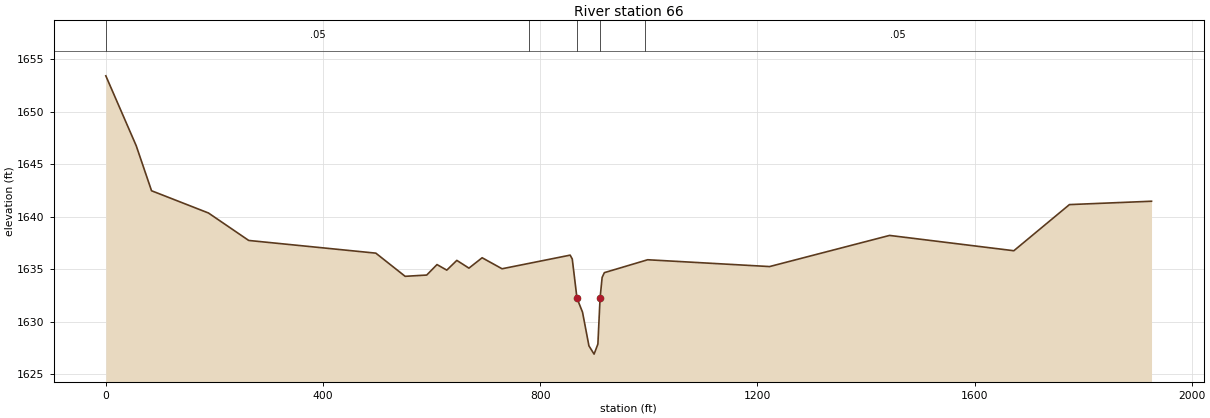
Type RM Length L Ch R = 1 ,66      ,64.05,66.12,68.19
XS GIS Cut Line= 5
2077871.06310686301742.7534737892077191.80987218301245.791869298
 2077096.3238427301182.8576119542076627.57379594301054.819482207
 2076143.6328347301065.670182288
#Sta/Elev= 30
       0 1653.43      56 1646.76    84.2 1642.47     189 1640.35   263.2 1637.73
   497.3 1636.52   551.3 1634.31     591 1634.43     610 1635.43     628  1634.9
   646.5 1635.83   668.8 1635.09   693.1 1636.08   729.8 1635.03   855.2 1636.33
   859.1 1635.96  867.781632.227     878 1630.89   889.8 1627.68   899.3 1626.89
   906.3 1627.85  910.321632.233   914.1  1634.2   918.2 1634.66     998 1635.89
  1222.5 1635.24  1443.5 1638.21  1672.4 1636.75  1774.8 1641.15    1926 1641.47
#Mann= 5 ,-1 , 0
       0     .05       0  779.21    .055       0  867.78    .045       0
  910.32    .055       0  992.31     .05       0
Bank Sta=867.78,910.32
XS Rating Curve= 0 ,0
Exp/Cntr=0.3,0.1
LCMann Table=0

Chan Stop Cuts=-1
Use User Specified Reach Order=0
Composite Channel Slope=5